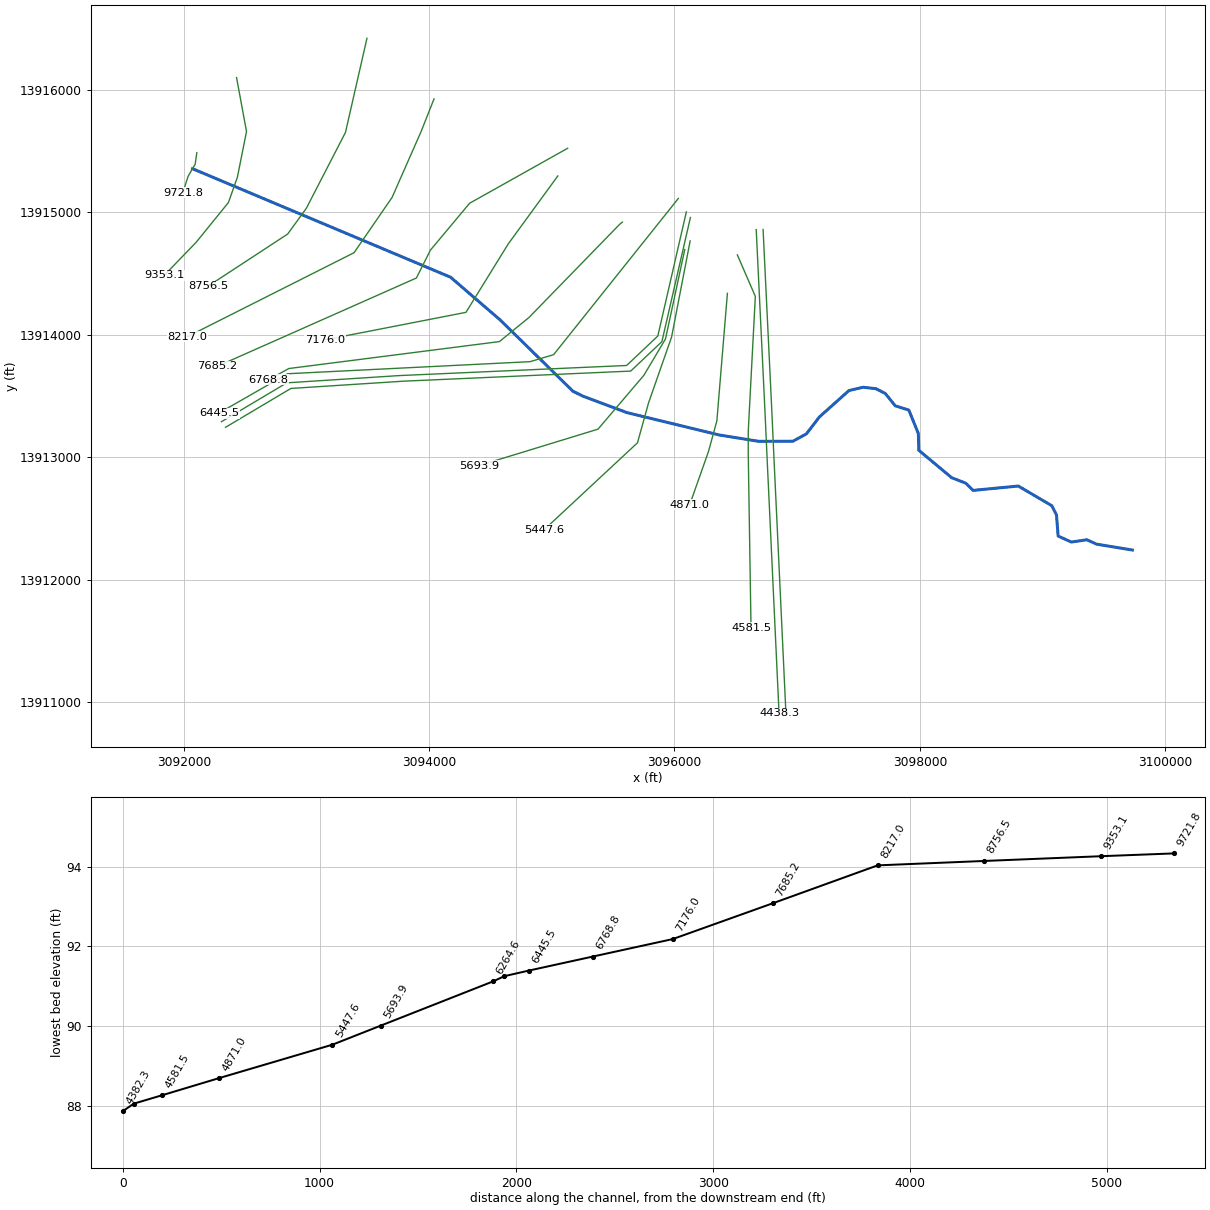
--- P146-00-00.prj (project) ---

Proj Title=P146-00-00
Current Plan=p01
Default Exp/Contr=.3,.1
English Units
Geom File=g01
Flow File=f02
Flow File=f01
Plan File=p02
Plan File=p01
Y Axis Title=Elevation
X Axis Title(PF)=Main Channel Distance
X Axis Title(XS)=Station
BEGIN DESCRIPTION:
HCFCD Watershed Unit ID: P
M3 Study Identifier: 2007_Effective_P
Engineer: HCFCD
Project Name: EffectiveFEMA Study for watershed Greens Bayou (P)
Study Completion Date: 6/18/2007
FEMA Case Number: [No Data]
FEMA Approval Date: [No Date in Database]
Vertical Datum: NAVD 1988
Datum Note: 2001 ADJ
HYDRAULICS
HCFCD Unit No.:  P146-00-00
Hydraulic Program Name: HEC-RAS
Hydraulic Program Version: 3.0.1
Steady Hydraulic Model: Yes
Unsteady Hydraulic Model: No
Update 1:
The effective FEMA hydraulic model for unit number P100-00-00 has been updated by FEMA LOMR 13-06-2759P with an effective date of 9/15/2014.
END DESCRIPTION:
DSS Export Rating Curves= 0
DSS Export Rating Curve Sorted= 0
DSS Export Volume Flow Curves= 0
DXF OffsetX= 0
DXF OffsetY= 0
DXF ScaleX= 1
DXF ScaleY= 10

--- P146-00-00.p01 (plan) ---

Plan Title=FEMA Effective Multi-Profile 2014
Program Version=4.10
Short Identifier=Eff+LOMR MP
Geom File=g01
Flow File=f01
Subcritical Flow
K Sum by GR= 0
Std Step Tol= 0.01
Critical Tol= 0.01
Num of Std Step Trials= 20
Max Error Tol= 0.3
Flow Tol Ratio= 0.001
Split Flow NTrial= 30
Split Flow Tol= 0.02
Split Flow Ratio= 0.02
Log Output Level= 0
Friction Slope Method= 1
Unsteady Friction Slope Method= 2
Unsteady Bridges Friction Slope Method= 1
Parabolic Critical Depth
Global Vel Dist= 0 , 0 , 0
Global Log Level= 0
CheckData=True
Encroach Param=-1 ,0,0, 0
BEGIN DESCRIPTION:
FEMA Effective June 2007 + LOMR 13-06-2759P
END DESCRIPTION:
Computation Interval=1HOUR
Output Interval=1HOUR
Run HTab= 0
Run UNet= 0
Run PostProcess= 0
Run WQNet= 0
UNET Theta= 1
UNET Theta Warmup= 1
UNET ZTol= 0.02
UNET ZSATol= 0.1
UNET MxIter= 20
UNET MaxInSteps= 20
UNET DtIC= 0
UNET DtMin= 0
UNET MaxCRTS= 20
UNET WFStab= 2
UNET SFStab= 1
UNET WFX= 1
UNET SFX= 1
UNET DSS MLevel= 4
UNET DZMax Abort= 100
UNET Convert EG Bridges=-1
UNET Use Existing IB Tables=-1
UNET Froude Reduction=False
UNET Froude Limit= 1
UNET Froude Power= 10
UNET Time Slicing=0,0, 5
UNET Junction Losses=0
Instantaneous Interval=1HOUR
Write IC File= 0
Write IC File at Sim End=0
Echo Input=False
Echo Parameters=False
Echo Output=False
Write Detailed= 0
WQ AD Non Conservative
WQ ULTIMATE=-1
WQ Max Comp Step=1HOUR
WQ Output Interval=15MIN
WQ Output Selected Increments= 0
WQ Output face flow=0
WQ Output face velocity=0
WQ Output face area=0
WQ Output face dispersion=0
WQ Output cell volume=0
WQ Output cell surface area=0
WQ Output cell continuity=0
WQ Output cumulative cell continuity=0
WQ Output face conc=0
WQ Output face dconc_dx=0
WQ Output face courant=0
WQ Output face peclet=0
WQ Output face adv mass=0
WQ Output face disp mass=0
WQ Output cell mass=0
WQ Output cell source sink temp=0
WQ Output cell source sink nsm=0
WQ Output MaxMinRange=-1
WQ Daily Max Min Mean=-1
WQ Daily Range=0
WQ Daily Time=0
WQ Create Restart=0
WQ Fixed Restart=0
WQ System Summary=0
WQ Use Fixed Temperature=0
Sorting and Armoring Iterations= 10
XS Update Threshold= 0.02
Hydraulics Update Threshold= 0.02
Energy Slope Method= 1
Volume Change Method= 0
XS Weighting Method= 0
Number of US Weighted Cross Sections= 1
Number of DS Weighted Cross Sections= 1
Upstream XS Weight=0.25
Main XS Weight=0.5
Downstream XS Weight=0.25
Number of DS XS's Weighted with US Boundary= 1
Upstream Boundary Weight= 1
Weight of XSs Associated with US Boundary= 0
Number of US XS's Weighted with DS Boundary= 1
Downstream Boundary Weight= 0.5
Weight of XSs Associated with DS Boundary= 0.5
Sediment Output Level= 4
Mass or Volume Output= 0
Output Increment Type= 1
Profile and TS Output Increment= 10
XS Output Flag= 0
XS Output Increment= 10
Disregard all LS=0
Disregard all Conn=0
Disregard all Breaches=0
Disregard all Pumps=0

--- P146-00-00.p02 (plan) ---

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Plan Title=FEMA Effective Floodway 2014
Short Identifier=Eff+LOMR FW
Geom File=g01
Flow File=f02
Encroach Param=-1 ,0,0, 2
Encroach River=P146-00-00
Encroach Reach=Reach - 1
Encroach Node=9721.8
       1  4987.5  5016.3
Encroach Node=9353.1
       1  4987.5  5016.4
Encroach Node=8756.5
       1  4984.5  5015.3
Encroach Node=8217.0
       1  4984.5  5015.3
Encroach Node=7685.2
       1  4982.1  5018.6
Encroach Node=7176.0
       1  4982.1  5018.6
Encroach Node=6768.8
       1  4982.1  5018.6
Encroach Node=6445.5
       1 4982.46 5019.61
Encroach Node=6321.2
       1 4982.46 5019.61
Encroach Node=6292.9
       1 4982.46 5019.61
Encroach Node=6264.6
       1 4982.46 5019.61
Encroach Node=5693.9
       1    4966  5021.9
Encroach Node=5447.6
       1  4969.2  5021.9
Encroach Node=4871.0
       1  4976.3  5025.2
Encroach Node=4581.5
       1  4976.3  5025.2
Encroach Node=4438.3
       1  4976.3  5025.2
Encroach Node=4410.3
       1  4976.3  5025.2
Encroach Node=4382.3
       1  4976.3  5025.2
Encroach Node=3638.6
       1  4981.2  5029.5
Encroach Node=3035.3
       1  4965.8  5023.4
Encroach Node=2484.4
       1    4979  5023.4
Encroach Node=1737.9
       1  4969.5  5021.9
Encroach Node=1284.9
       1  4969.5  5021.9
Encroach Node=607.3
       1    4980  5023.6
Encroach Reach=P146-00-00_0006
Encroach Node=9721.8
       1  4987.5  5016.3
Encroach Node=9353.1
       1  4987.5  5016.4
Encroach Node=8756.5
       1  4984.5  5015.3
Encroach Node=8217.0
       1  4984.5  5015.3
Encroach Node=7685.2
       1  4982.1  5018.6
Encroach Node=7176.0
       1  4982.1  5018.6
Encroach Node=6768.8
       1  4982.1  5018.6
Encroach Node=6445.5
       1 4982.46 5019.61
Encroach Node=6321.2
       1 4982.46 5019.61
Encroach Node=6292.9
       1 4982.46 5019.61
Encroach Node=6264.6
       1 4982.46 5019.61
Encroach Node=5693.9
       1    4966  5021.9
Encroach Node=5447.6
       1  4969.2  5021.9
Encroach Node=4871.0
       1  4976.3  5025.2
Encroach Node=4581.5
       1  4976.3  5025.2
Encroach Node=4438.3
       1  4976.3  5025.2
Encroach Node=4410.3
       1  4976.3  5025.2
Encroach Node=4382.3
       1  4976.3  5025.2
Encroach Node=3638.6
       1  4981.2  5029.5
Encroach Node=3035.3
       1  4965.8  5023.4
Encroach Node=2484.4
       1    4979  5023.4
Encroach Node=1737.9
       1  4969.5  5021.9
Encroach Node=1578.978
       1  4989.8  5035.8
Encroach Node=1548.856
       1 4964.65 5026.65
Encroach Node=1488.33
       1    4964    5045
Encroach Node=1427.807
       1  4978.8  5045.8
Encroach Node=1340.462
       1  4970.1  5021.1
Encroach Node=1274.486
       1  4958.6  5007.6
Encroach Node=607.3
       1    4980  5023.6

--- P146-00-00.f01 (steady flow) ---

Flow Title=FEMA Effective June 2007
Program Version=4.10
Number of Profiles= 4
Profile Names=10PCT_10yr, 2PCT_50yr, 1PCT_100yr, 0.2PCT_500yr
River Rch & RM=P146-00-00,P146-00-00_0006 ,9721.8
      29      42      49      68
River Rch & RM=P146-00-00,P146-00-00_0006 ,8756.5
      33      49      57      79
River Rch & RM=P146-00-00,P146-00-00_0006 ,8217
      39      57      66      91
River Rch & RM=P146-00-00,P146-00-00_0006 ,7685.2
      44      65      76     105
River Rch & RM=P146-00-00,P146-00-00_0006 ,7176
      50      73      84     118
River Rch & RM=P146-00-00,P146-00-00_0006 ,6768.8
      54      80      92     129
River Rch & RM=P146-00-00,P146-00-00_0006 ,6445.5
      56      82      96     133
River Rch & RM=P146-00-00,P146-00-00_0006 ,6321.2
      67      98     114     158
River Rch & RM=P146-00-00,P146-00-00_0006 ,5693.9
      71     105     122     169
River Rch & RM=P146-00-00,P146-00-00_0006 ,5447.6
      84     123     143     199
River Rch & RM=P146-00-00,P146-00-00_0006 ,4871
      91     133     154     215
River Rch & RM=P146-00-00,P146-00-00_0006 ,4581.5
      94     138     161     224
River Rch & RM=P146-00-00,P146-00-00_0006 ,4438.3
     118     172     200     279
River Rch & RM=P146-00-00,P146-00-00_0006 ,3638.6
     139     204     236     330
River Rch & RM=P146-00-00,P146-00-00_0006 ,3035.3
     162     237     275     384
River Rch & RM=P146-00-00,P146-00-00_0006 ,2484.4
     199     291     338     471
River Rch & RM=P146-00-00,P146-00-00_0006 ,1737.9
     225     330     383     534
River Rch & RM=P146-00-00,P146-00-00_0006 ,1274.486
     271     398     462     644
Boundary for River Rch & Prof#=P146-00-00,P146-00-00_0006 , 1
Up Type= 0
Dn Type= 3
Dn Slope=0.0022
Boundary for River Rch & Prof#=P146-00-00,P146-00-00_0006 , 2
Up Type= 0
Dn Type= 3
Dn Slope=0.0022
Boundary for River Rch & Prof#=P146-00-00,P146-00-00_0006 , 3
Up Type= 0
Dn Type= 3
Dn Slope=0.0022
Boundary for River Rch & Prof#=P146-00-00,P146-00-00_0006 , 4
Up Type= 0
Dn Type= 3
Dn Slope=0.0022
DSS Import GetInterval= 0
DSS Import GetPeak= 0
DSS Import FillOption= 0

--- P146-00-00.f02 (steady flow) ---

Flow Title=Floodway
Program Version=4.10
Number of Profiles= 2
Profile Names=1PCT_100yr, 1PCTFloodway_100yrFW
River Rch & RM=P146-00-00,P146-00-00_0006 ,9721.8
      49      49
River Rch & RM=P146-00-00,P146-00-00_0006 ,8756.5
      57      57
River Rch & RM=P146-00-00,P146-00-00_0006 ,8217
      66      66
River Rch & RM=P146-00-00,P146-00-00_0006 ,7685.2
      76      76
River Rch & RM=P146-00-00,P146-00-00_0006 ,7176
      84      84
River Rch & RM=P146-00-00,P146-00-00_0006 ,6768.8
      92      92
River Rch & RM=P146-00-00,P146-00-00_0006 ,6445.5
      96      96
River Rch & RM=P146-00-00,P146-00-00_0006 ,6321.2
     114     114
River Rch & RM=P146-00-00,P146-00-00_0006 ,5693.9
     122     122
River Rch & RM=P146-00-00,P146-00-00_0006 ,5447.6
     143     143
River Rch & RM=P146-00-00,P146-00-00_0006 ,4871
     154     154
River Rch & RM=P146-00-00,P146-00-00_0006 ,4581.5
     161     161
River Rch & RM=P146-00-00,P146-00-00_0006 ,4438.3
     200     200
River Rch & RM=P146-00-00,P146-00-00_0006 ,3638.6
     236     236
River Rch & RM=P146-00-00,P146-00-00_0006 ,3035.3
     275     275
River Rch & RM=P146-00-00,P146-00-00_0006 ,2484.4
     338     338
River Rch & RM=P146-00-00,P146-00-00_0006 ,1737.9
     383     383
River Rch & RM=P146-00-00,P146-00-00_0006 ,1274.486
     462     462
Boundary for River Rch & Prof#=P146-00-00,P146-00-00_0006 , 1
Up Type= 0
Dn Type= 3
Dn Slope=0.0022
Boundary for River Rch & Prof#=P146-00-00,P146-00-00_0006 , 2
Up Type= 0
Dn Type= 1
Dn Known WS=89.18
DSS Import GetInterval= 0
DSS Import GetPeak= 0
DSS Import FillOption= 0

--- P146-00-00.g01 (geometry) ---

Geom Title=P146-00-00
Program Version=4.10

River Reach=P146-00-00      ,P146-00-00_0006
Reach XY= 30
      3092070.81     13915357.49       3094174.5       13914471.
       3094577.5       13914123.       3095171.5       13913540.
      3095254.25       13913499.      3095611.75       13913365.
       3096364.5       13913182.       3096687.5       13913130.
      3096965.75       13913131.      3097075.64     13913191.13
      3097180.98      13913328.9      3097422.25       13913545.
       3097538.5       13913572.       3097642.5       13913560.
      3097718.75       13913521.      3097799.38      13913420.3
      3097910.49     13913385.75      3097987.99     13913194.34
      3097991.72     13913057.08       3098259.7     13912832.99
      3098374.55     13912788.17      3098434.31     13912729.35
      3098803.12     13912764.83      3099076.25       13912604.
      3099114.25       13912529.      3099127.73      13912355.9
      3099235.51     13912307.19      3099361.94     13912325.85
      3099441.25       13912290.      3099733.25       13912242.

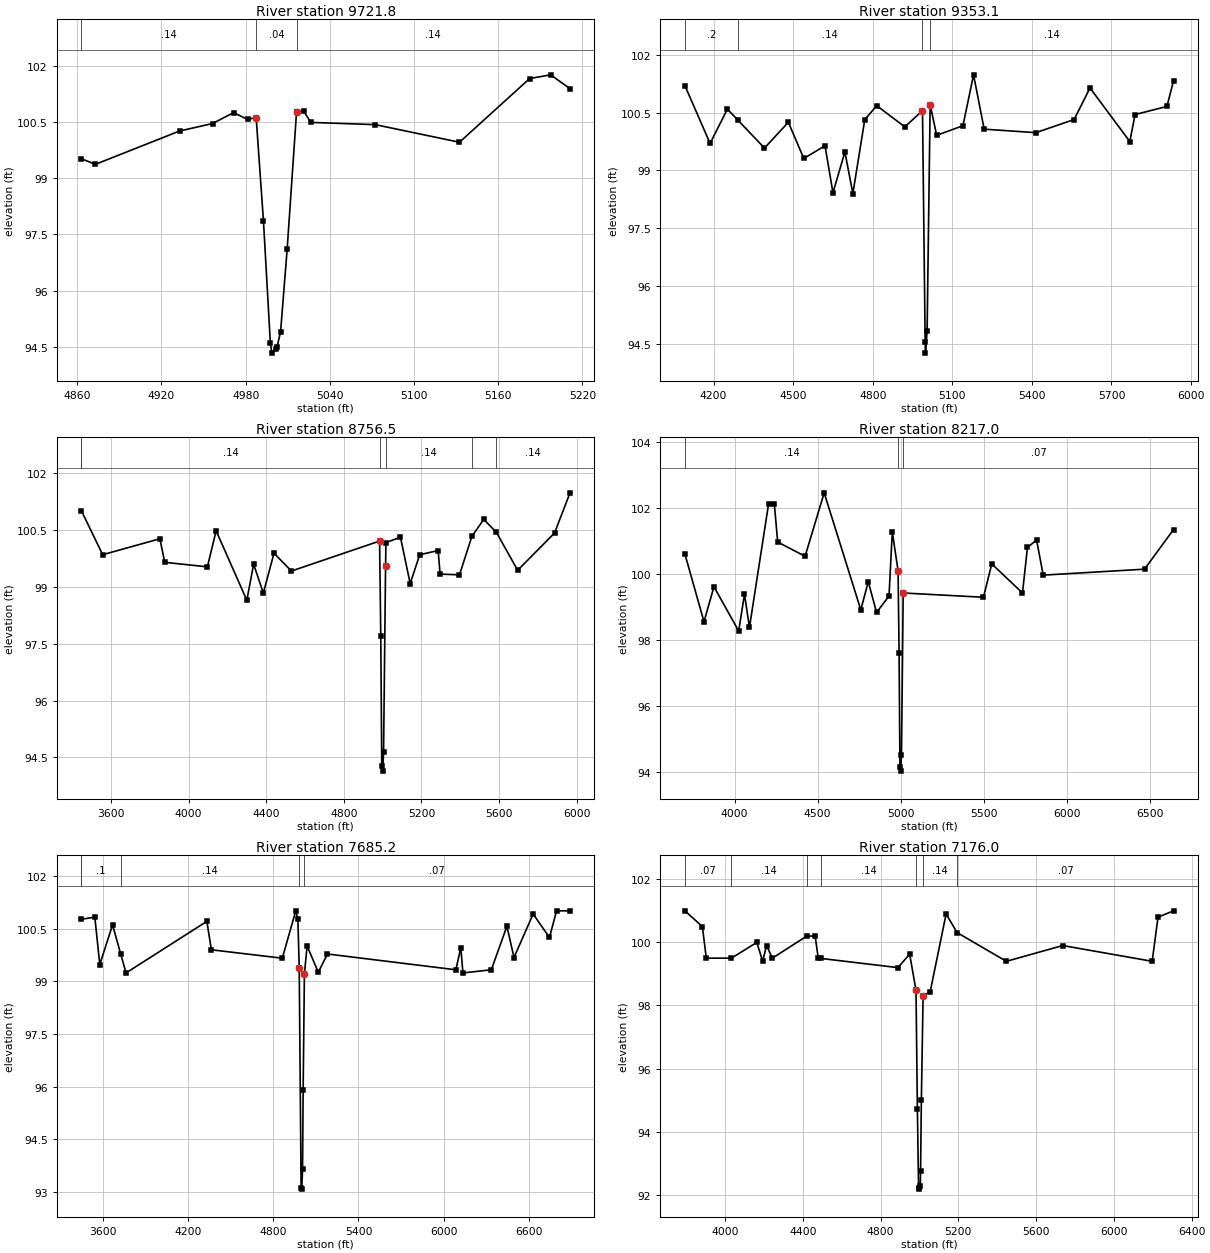
Type RM Length L Ch R = 1 ,9721.8  ,376,368.7,366
BEGIN DESCRIPTION:
Cross Section 9721.8 - Interpolated
END DESCRIPTION:
XS GIS Cut Line= 4
      3092105.84     13915487.78      3092092.62     13915395.25
      3092034.46     13915294.79      3091992.16     13915162.61
#Sta/Elev= 23
  4862.9   99.52  4872.9   99.37  4932.9  100.26  4956.4  100.46  4971.4  100.75
  4981.4  100.57  4987.5  100.62  4992.7   97.86  4997.6   94.61  4998.7   94.33
  5001.3   94.44  5002.4    94.5  5004.9    94.9  5009.6   97.11  5016.3  100.78
  5016.4  100.78  5021.4  100.79  5026.4  100.49  5072.4  100.43  5132.4   99.96
  5182.4  101.66  5197.4  101.76  5211.2  101.39
#Mann= 3 , 1 , 0
  4862.9     .14       0  4987.5     .04       0  5016.3     .14       0
Bank Sta=4987.5,5016.3
XS Rating Curve= 0 ,0
Exp/Cntr=0.3,0.1

Type RM Length L Ch R = 1 ,9353.1  ,707.2,596.6,490.2
BEGIN DESCRIPTION:
Cross Section  9353.1
END DESCRIPTION:
XS GIS Cut Line= 6
      3092429.69     13916102.31      3092510.88     13915661.57
      3092436.54     13915287.99      3092363.53     13915081.39
      3092099.87     13914755.83       3091839.6     13914485.73
#Sta/Elev= 30
  4091.8   101.2  4186.8    99.7  4251.8  100.59  4292.2   100.3  4391.8   99.58
  4481.8  100.25    4540   99.31    4620   99.64    4650   98.42    4695   99.48
    4725    98.4    4770  100.32    4815  100.68  4920.9  100.13  4987.5  100.55
  4997.6   94.54  4998.7   94.26  5004.9   94.83  5016.4  100.71  5040.8   99.91
    5140  100.16    5180  101.48    5220  100.07    5415   99.98    5559  100.32
    5619  101.14    5769   99.75    5789  100.45    5909  100.66    5934  101.33
#Mann= 4 , 1 , 0
  4091.8      .2       0  4292.2     .14       0  4987.5     .04       0
  5016.4     .14       0
Bank Sta=4987.5,5016.4
XS Rating Curve= 0 ,0
Exp/Cntr=0.3,0.1

Type RM Length L Ch R = 1 ,8756.5  ,581.8,539.5,421.6
BEGIN DESCRIPTION:
Cross Section 8756.5-Interpolated
END DESCRIPTION:
XS GIS Cut Line= 5
      3093492.74      13916422.7      3093317.68     13915653.96
      3092998.55       13915034.      3092846.54     13914823.88
       3092198.7     13914398.53
#Sta/Elev= 30
  3446.5     101  3556.5   99.84  3851.5  100.26  3876.5   99.64  4096.5   99.52
  4141.5  100.47  4299.9   98.64  4334.9   99.59  4384.9   98.83  4439.9   99.88
  4529.9   99.41  4984.5   100.2  4990.6   97.71  4995.7   94.28  5000.7   94.14
    5005   94.64  5015.3   99.53  5017.2  100.16  5092.2   100.3  5142.2   99.08
  5191.5   99.84  5286.5   99.95  5296.5   99.33  5396.5   99.31  5460.2  100.32
  5521.5  100.77  5586.8  100.43  5696.5   99.43  5886.5  100.41  5966.5  101.47
#Mann= 6 , 1 , 0
  3446.5      .2       0  3446.5     .14       0  4984.5     .04       0
  5015.3     .14       0  5460.2     .07       0  5586.8     .14       0
Bank Sta=4984.5,5015.3
XS Rating Curve= 0 ,0
Exp/Cntr=0.3,0.1

Type RM Length L Ch R = 1 ,8217.0  ,540.9,531.8,508.9
BEGIN DESCRIPTION:
Cross Section  8217.0
END DESCRIPTION:
XS GIS Cut Line= 5
      3094039.73     13915928.42      3093935.52     13915664.33
      3093698.06      13915123.6      3093387.42     13914671.07
      3092030.59     13913986.07
#Sta/Elev= 30
  3700.5   100.6  3815.5   98.55  3875.5   99.61  4024.4   98.27  4059.4   99.38
  4089.4   98.38  4204.4  102.11  4239.4   102.1  4259.4  100.96  4424.4  100.53
  4539.4  102.45    4760   98.91    4805   99.76    4855   98.83    4930   99.33
  4949.7  101.27  4984.5  100.09  4990.6    97.6  4995.7   94.17  5000.7   94.03
    5005   94.53  5015.3   99.42  5498.8   99.29  5548.8   100.3  5733.8   99.42
  5763.8   100.8  5818.8  101.02  5858.8   99.96  6468.8  100.14  6643.8  101.34
#Mann= 3 , 1 , 0
  3700.5     .14       0  4984.5     .04       0  5015.3     .07       0
#XS Ineff= 2 , 0
       0    4124    99.5               0
Permanent Ineff=
       F       F
Bank Sta=4984.5,5015.3
XS Rating Curve= 0 ,0
Exp/Cntr=0.3,0.1

Type RM Length L Ch R = 1 ,7685.2  ,472.3,509.2,435.6
BEGIN DESCRIPTION:
Cross Section 7685.2-Interpolated
END DESCRIPTION:
XS GIS Cut Line= 5
      3095129.17     13915524.57      3094329.98      13915075.5
      3094009.59      13914691.5      3093896.12     13914464.56
      3092274.11     13913743.66
#Sta/Elev= 30
  3445.9  100.77  3540.9  100.83  3575.9   99.48  3665.9  100.61  3724.1   99.77
  3760.9   99.24  4330.9  100.71  4362.6    99.9  4862.7   99.66  4957.7  101.01
  4972.7  100.77  4982.1   99.38  4995.4   93.11  4999.6   93.08  5005.6   93.64
  5009.7   95.91  5018.6   99.21  5037.7  100.01  5116.4   99.26  5181.4   99.78
  6086.4   99.33  6121.4   99.96  6136.4   99.24  6336.4   99.33  6446.4  100.57
  6496.4   99.68  6631.4  100.92  6746.4  100.25  6796.4  101.01  6891.4  101.01
#Mann= 5 , 1 , 0
  3445.9      .2       0  3445.9      .1       0  3724.1     .14       0
  4982.1     .04       0  5018.6     .07       0
Bank Sta=4982.1,5018.6
XS Rating Curve= 0 ,0
Exp/Cntr=0.3,0.1

Type RM Length L Ch R = 1 ,7176.0  ,520.2,407.2,312.3
BEGIN DESCRIPTION:
Cross Section  7176.0
END DESCRIPTION:
XS GIS Cut Line= 4
      3095048.93     13915298.54      3094645.32     13914743.93
      3094300.16     13914184.02      3093151.85     13913959.68
#Sta/Elev= 30
  3793.3     101  3883.3   100.5  3903.3    99.5  4032.7    99.5  4163.3     100
  4193.3    99.4  4213.3    99.9  4243.3    99.5  4420.3   100.2  4463.3   100.2
  4479.2    99.5  4494.7   99.49  4889.2    99.2  4949.5   99.63  4982.1   98.48
  4989.2   94.72  4995.4   92.21  4999.6   92.18  5004.1   92.29  5005.6   92.74
  5009.7   95.01  5018.6   98.31  5054.9   98.43    5137   100.9  5193.5  100.31
    5447    99.4    5737    99.9    6197    99.4    6227   100.8    6307     101
#Mann= 7 , 1 , 0
  3793.3     .07       0  4032.7     .14       0  4420.3      .1       0
  4494.7     .14       0  4982.1     .05       0  5018.6     .14       0
  5193.5     .07       0
Bank Sta=4982.1,5018.6
XS Rating Curve= 0 ,0
Exp/Cntr=0.3,0.1

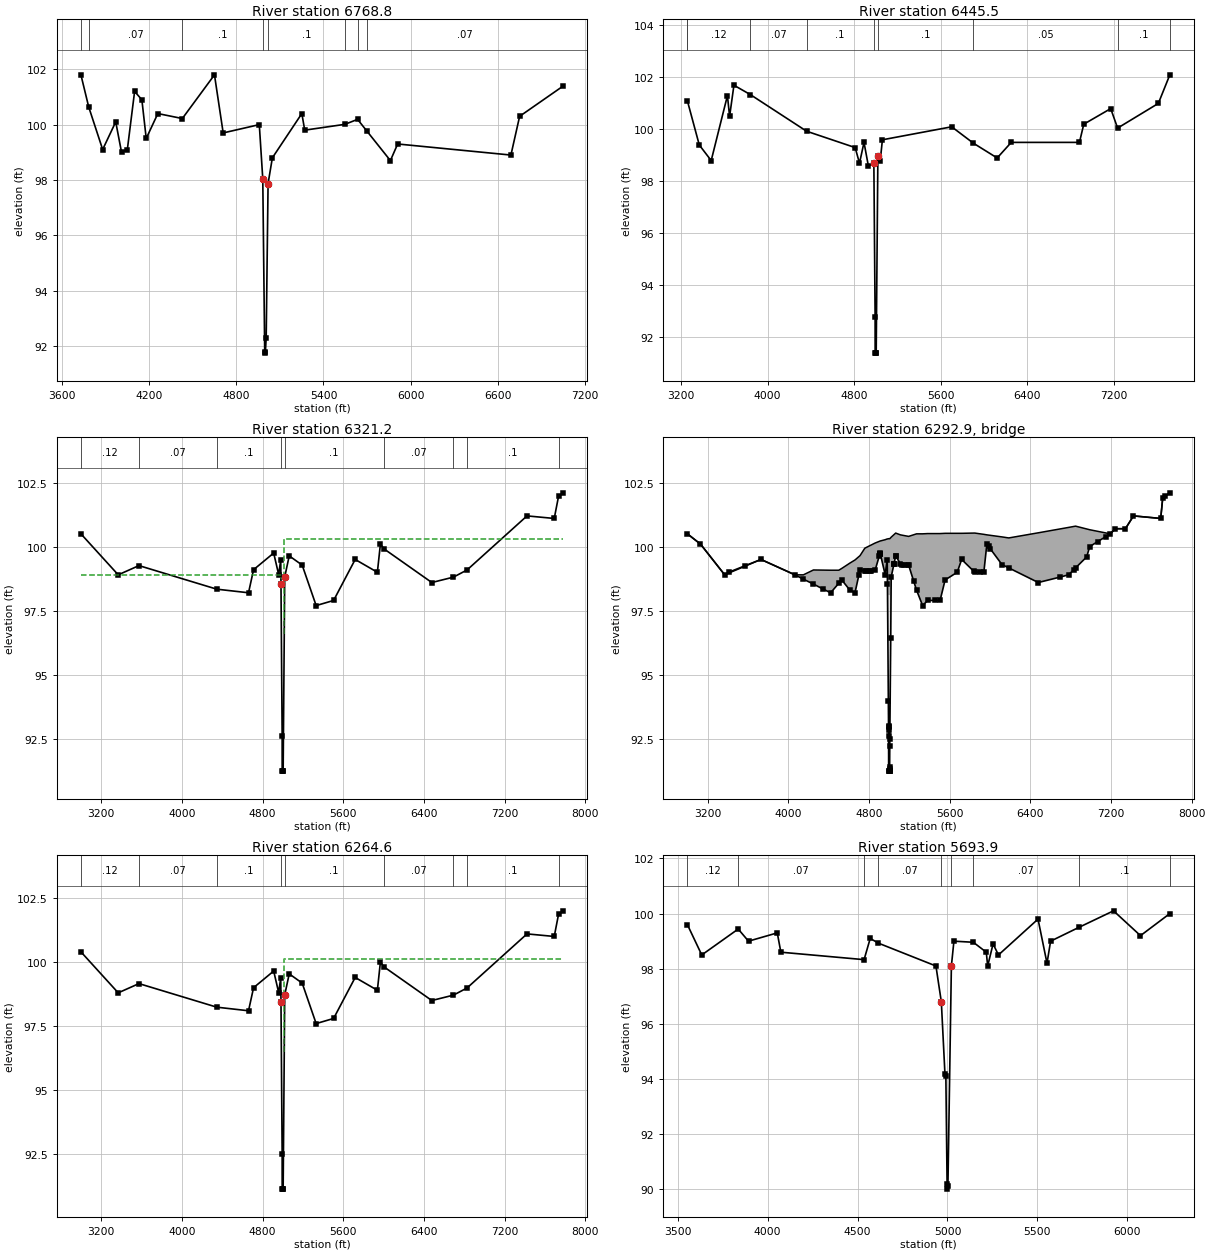
Type RM Length L Ch R = 1 ,6768.8  ,323.9,323.3,211.2
BEGIN DESCRIPTION:
Cross Section 6768.8-Interpolated
END DESCRIPTION:
XS GIS Cut Line= 6
       3095575.6     13914921.55      3095552.53     13914902.73
      3094815.03     13914143.22      3094572.86     13913945.09
       3092855.7     13913724.94      3092689.55     13913632.63
#Sta/Elev= 30
  3729.6   101.8  3783.2  100.64  3879.4    99.1  3969.4   100.1  4009.4      99
  4049.4    99.1  4099.4   101.2  4149.4   100.9  4179.4    99.5  4259.4   100.4
    4428  100.22  4649.4   101.8  4709.4    99.7  4958.1     100  4982.1   98.04
  4995.4   91.77  4999.6   91.74  5005.6    92.3  5018.6   97.87  5048.1    98.8
    5251   100.4    5271    99.8  5547.3  100.01  5634.9  100.19  5697.1   99.78
    5861    98.7    5911    99.3    6691    98.9    6751   100.3  7052.2   101.4
#Mann= 8 , 1 , 0
  3729.6     .12       0  3783.2     .07       0    4428      .1       0
  4982.1     .05       0  5018.6      .1       0  5547.3     .07       0
  5634.9      .1       0  5697.1     .07       0
Bank Sta=4982.1,5018.6
XS Rating Curve= 0 ,0
Exp/Cntr=0.3,0.1

Type RM Length L Ch R = 1 ,6445.5  ,514.9,124.3,118.2
BEGIN DESCRIPTION:
Cross Section 6445.5-Interpolated
END DESCRIPTION:
XS GIS Cut Line= 5
      3096031.18     13915114.23      3095014.42     13913838.08
      3094822.48     13913781.02        3092846.     13913682.45
      3092285.74     13913360.82
#Sta/Elev= 30
  3259.7   101.1  3369.7    99.4  3479.7    98.8  3629.7   101.3  3649.7   100.5
  3689.7   101.7  3841.1  101.34  4360.9   99.93  4809.7    99.3  4849.7    98.7
  4891.4    99.5  4931.4    98.6 4982.46    98.7 4994.03   92.78 4994.26   91.41
 4999.39   91.39 5003.98    91.4 5019.61   98.97  5041.4    98.8  5061.4    99.6
  5701.6   100.1  5901.6   99.47  6121.6    98.9  6251.6    99.5  6881.6    99.5
  6921.6   100.2  7170.5   100.8  7234.1  100.05  7610.5     101  7716.6   102.1
#Mann= 9 , 1 , 0
  3259.7      .2       0  3259.7     .12       0  3841.1     .07       0
  4360.9      .1       0 4982.46     .05       0 5019.61      .1       0
  5901.6     .05       0  7234.1      .1       0  7716.6      .2       0
Bank Sta=4982.46,5019.61
XS Rating Curve= 0 ,0
Exp/Cntr=0.5,0.3

Type RM Length L Ch R = 1 ,6321.2  ,56.6,56.6,56.6
BEGIN DESCRIPTION:
Upstream Section of Bridge/Culvert/Weir
END DESCRIPTION:
XS GIS Cut Line= 6
      3096096.59     13915004.61      3095864.07     13913990.41
       3095609.9     13913749.93      3093756.55     13913667.35
      3092839.39     13913608.09      3092306.48      13913290.4
#Sta/Elev= 30
    2998  100.51    3368   98.91  3573.8   99.27  4345.9   98.35  4660.5   98.21
  4710.5   99.11 4910.07   99.76 4959.56   98.92 4980.16    99.5 4982.46   98.56
 4994.03   92.64 4994.26   91.27 4999.39   91.25 5003.98   91.26 5019.61   98.83
 5064.19   99.65 5192.65   99.29  5331.3   97.71  5504.5   97.91  5718.6   99.51
  5938.6   99.01  5968.6  100.11  6001.9   99.93  6478.6   98.61    6693   98.82
  6828.3    99.1  7422.9  101.21  7692.9  101.11  7735.4  101.97  7783.4  102.11
#Mann= 9 , 1 , 0
    2998     .12       0  3573.8     .07       0  4345.9      .1       0
 4982.46     .05       0 5019.61      .1       0  6001.9     .07       0
    6693     .14       0  6828.3      .1       0  7735.4      .2       0
#XS Ineff= 2 , 0
       0    4982    98.9    5015       0   100.3
Permanent Ineff=
       F       F
Bank Sta=4982.46,5019.61
XS Rating Curve= 0 ,0
Exp/Cntr=0.5,0.3

Type RM Length L Ch R = 3 ,6292.9  ,,,
BEGIN DESCRIPTION:
HUGH ROAD, SKEW ANGLE OF 40 DEGREES
Structure ID: P46-3,,,,
END DESCRIPTION:
Bridge Culvert--1,0,-1,-1, 0
Deck Dist Width WeirC Skew NumUp NumDn MinLoCord MaxHiCord MaxSubmerge Is_Ogee
10,36.6,2.6,0, 53, 53, , , 0.95, 0, 1,1,,
    2998    3128    3368    3728  4064.7  4148.5  4248.5  4419.3  4499.6  4529.3
  4610.5  4660.5  4710.5  4758.2 4859.52 4910.07 4959.56 4980.16 4982.46 4993.32
 4993.41  5004.1 5004.21  5005.9 5015.01 5019.61 5064.19 5110.92 5192.65  5271.3
  5331.3  5381.3  5504.5  5554.5  5674.5  5718.6  5848.6  5938.6  5968.6  6118.6
  6185.9  6478.6  6778.6  6848.5  6958.6  6988.6  7192.9  7242.9  7342.9  7422.9
  7692.9  7712.9  7783.4
   100.5   100.1    98.9    99.5    98.9    98.9   99.09   99.08   99.08   99.15
   99.36   99.48   99.65   99.94  100.14  100.22  100.27   100.3   100.3  100.31
  100.31  100.31  100.31  100.31  100.35  100.37  100.53  100.46   100.4   100.5
   100.5  100.51  100.51  100.52  100.52  100.52  100.53  100.48  100.46  100.38
  100.34  100.54  100.75   100.8  100.69  100.66   100.5   100.7   100.7   101.2
   101.1   101.9   102.1
   100.5   100.1    98.9    99.5    98.9   98.73   98.54    98.2   98.57    98.7
    98.3    98.2    99.1   99.05   99.07   99.75   98.91   99.49   98.55   92.99
   98.11   98.11    91.4    92.5   96.42   98.82   99.64   99.33   99.28    98.3
    97.7    97.9    97.9    98.7      99    99.5      99      99   100.1    99.3
   99.17    98.6    98.9   99.17    99.6     100   100.5   100.7   100.7   101.2
   101.1   101.9   102.1
    2998    3128    3368    3728  4064.7  4148.5  4248.5  4419.3  4499.6  4529.3
  4610.5  4660.5  4710.5  4758.2 4859.52 4910.07 4959.56 4980.16 4982.46 4993.32
 4993.41  5004.1 5004.21  5005.9 5015.01 5019.61 5064.19 5110.92 5192.65  5271.3
  5331.3  5381.3  5504.5  5554.5  5674.5  5718.6  5848.6  5938.6  5968.6  6118.6
  6185.9  6478.6  6778.6  6848.5  6958.6  6988.6  7192.9  7242.9  7342.9  7422.9
  7692.9  7712.9  7783.4
   100.5   100.1    98.9    99.5    98.9    98.9   99.09   99.08   99.08   99.15
   99.36   99.48   99.65   99.94  100.14  100.22  100.27   100.3   100.3  100.31
  100.31  100.31  100.31  100.31  100.35  100.37  100.53  100.46   100.4   100.5
   100.5  100.51  100.51  100.52  100.52  100.52  100.53  100.48  100.46  100.38
  100.34  100.54  100.75   100.8  100.69  100.66   100.5   100.7   100.7   101.2
   101.1   101.9   102.1
   100.4     100    98.8    99.4    98.8   98.63   98.44    98.1   98.47    98.6
    98.2    98.1      99   98.95   98.97   99.65   98.81   99.39   98.45   92.89
   98.01   98.01    91.3    92.4   96.32   98.72   99.54   99.23   99.18    98.2
    97.6    97.8    97.8    98.6    98.9    99.4    98.9    98.9     100    99.2
   99.07    98.5    98.8   99.07    99.5    99.9   100.4   100.6   100.6   101.1
     101   101.8     102
BR Coef= 1 , 1 , 0 ,1.25, 0 ,,,0.8,0,2,0,
WSPro=,,,, 1 ,,,, 0 ,,,, 0 ,,,,-1 ,-1 ,-1 , 0 , 0 , 0 , 0 , 0
BR U #Sta/Elev= 91
    2998   100.5    3128   100.1    3368    98.9    3408      99  3573.8   99.26
    3728    99.5  4064.7    98.9  4148.5   98.73  4248.5   98.54  4345.9   98.34
  4419.3    98.2  4499.6   98.57  4529.3    98.7  4610.5    98.3  4660.5    98.2
  4698.4   98.88  4710.5    99.1  4758.2   99.05 4769.28   99.04 4811.87   99.06
  4821.6   99.06 4859.52   99.07  4902.5   99.65 4910.07   99.75 4912.79    99.7
  4912.9    99.7 4913.01    99.7 4959.56   98.91 4980.16   99.49 4982.46   98.55
  4991.4   93.98 4993.32   92.99 4993.41   92.95 4993.64   92.83 4994.03   92.63
 4994.26   91.26 4999.39   91.24 5003.52   91.25 5003.88   91.25 5003.98   91.25
  5004.1   91.33 5004.21    91.4  5005.5   92.24  5005.9    92.5 5015.01   96.42
 5019.61   98.82 5046.49   99.31  5046.6   99.32 5046.71   99.32  5063.3   99.62
 5064.19   99.64 5110.92   99.33    5128    99.3 5149.91   99.27  5186.4   99.28
 5192.65   99.28  5241.3   98.67  5271.3    98.3  5331.3    97.7  5381.3    97.9
  5451.3    97.9  5504.5    97.9  5554.5    98.7  5674.5      99  5718.6    99.5
  5840.9   99.03  5848.6      99  5895.9      99  5938.6      99  5968.6   100.1
  5985.9  100.01  6001.9   99.92  6118.6    99.3  6185.9   99.17  6478.6    98.6
    6693   98.81  6778.6    98.9  6828.3   99.09  6848.5   99.17  6958.6    99.6
  6988.6     100  7068.6   100.2  7148.5  100.39  7192.9   100.5  7242.9   100.7
  7342.9   100.7  7422.9   101.2  7692.9   101.1  7712.9   101.9  7735.4  101.96
  7783.4   102.1
BR U #Mann= 9
    2998     .12  3573.8     .07  4345.9      .1 4982.46     .05 5019.61      .1
  6001.9     .07    6693     .14  6828.3      .1  7735.4      .2
BR U Banks=4982.46,5019.61
BR D #Sta/Elev= 91
    2998   100.4    3128     100    3368    98.8    3408    98.9  3573.8   99.16
    3728    99.4  4064.7    98.8  4148.5   98.63  4248.5   98.44  4345.9   98.24
  4419.3    98.1  4499.6   98.47  4529.3    98.6  4610.5    98.2  4660.5    98.1
  4698.4   98.78  4710.5      99  4758.2   98.95 4769.28   98.94 4811.87   98.96
  4821.6   98.96 4859.52   98.97  4902.5   99.55 4910.07   99.65 4912.79    99.6
  4912.9    99.6 4913.01    99.6 4959.56   98.81 4980.16   99.39 4982.46   98.45
  4991.4   93.88 4993.32   92.89 4993.41   92.85 4993.64   92.73 4994.03   92.53
 4994.26   91.16 4999.39   91.14 5003.52   91.15 5003.88   91.15 5003.98   91.15
  5004.1   91.23 5004.21    91.3  5005.5   92.14  5005.9    92.4 5015.01   96.32
 5019.61   98.72 5046.49   99.21  5046.6   99.22 5046.71   99.22  5063.3   99.52
 5064.19   99.54 5110.92   99.23    5128    99.2 5149.91   99.17  5186.4   99.18
 5192.65   99.18  5241.3   98.57  5271.3    98.2  5331.3    97.6  5381.3    97.8
  5451.3    97.8  5504.5    97.8  5554.5    98.6  5674.5    98.9  5718.6    99.4
  5840.9   98.93  5848.6    98.9  5895.9    98.9  5938.6    98.9  5968.6     100
  5985.9   99.91  6001.9   99.82  6118.6    99.2  6185.9   99.07  6478.6    98.5
    6693   98.71  6778.6    98.8  6828.3   98.99  6848.5   99.07  6958.6    99.5
  6988.6    99.9  7068.6   100.1  7148.5  100.29  7192.9   100.4  7242.9   100.6
  7342.9   100.6  7422.9   101.1  7692.9     101  7712.9   101.8  7735.4  101.86
  7783.4     102
BR D #Mann= 9
    2998     .12  3573.8     .07  4345.9      .1 4982.46     .05 5019.61      .1
  6001.9     .07    6693     .14  6828.3      .1  7735.4      .2
BR D Banks=4982.46,5019.61
BC Design=,, 0 ,, 0 ,,,,,,
BC HTab HWMax=102.11
BC Use User HTab Curves=0
BC User HTab FreeFlow(D)= 0

Type RM Length L Ch R = 1 ,6264.6  ,570.7,570.7,570.7
BEGIN DESCRIPTION:
Downstream Section of Bridge/Culvert/Weir
END DESCRIPTION:
XS GIS Cut Line= 6
      3096129.81     13914958.78      3095897.29     13913944.59
      3095643.12     13913704.11      3093789.77     13913621.53
      3092872.61     13913562.27       3092339.7     13913244.58
#Sta/Elev= 30
    2998  100.38    3368   98.78  3573.8   99.14  4345.9   98.22  4660.5   98.08
  4710.5   98.98 4910.07   99.63 4959.56   98.79 4980.16   99.37 4982.46   98.43
 4994.03   92.51 4994.26   91.14 4999.39   91.12 5003.98   91.13 5019.61    98.7
 5064.19   99.52 5192.65   99.16  5331.3   97.58  5504.5   97.78  5718.6   99.38
  5938.6   98.88  5968.6   99.98  6001.9    99.8  6478.6   98.48    6693   98.69
  6828.3   98.97  7422.9  101.08  7692.9  100.98  7735.4  101.84  7783.4  101.98
#Mann= 9 , 1 , 0
    2998     .12       0  3573.8     .07       0  4345.9      .1       0
 4982.46     .05       0 5019.61      .1       0  6001.9     .07       0
    6693     .14       0  6828.3      .1       0  7735.4      .2       0
#XS Ineff= 2 , 0
       0    4982    98.5    5015       0   100.1
Permanent Ineff=
       F       F
Bank Sta=4982.46,5019.61
XS Rating Curve= 0 ,0
Exp/Cntr=0.5,0.3

Type RM Length L Ch R = 1 ,5693.9  ,216.2,246.3,264.8
BEGIN DESCRIPTION:
Cross Section 5693.9-Interpolated
END DESCRIPTION:
XS GIS Cut Line= 5
      3096083.86     13914697.51      3095926.78      13913967.1
      3095750.66      13913669.9      3095376.41      13913229.6
      3094407.75      13912932.4
#Sta/Elev= 30
  3553.4    99.6  3633.4    98.5  3836.1   99.44  3893.4      99  4053.4    99.3
  4073.4    98.6  4536.3   98.33  4570.5    99.1  4615.1   98.93    4936    98.1
    4966    96.8    4986    94.2  4991.2   94.11    4998   90.21  4999.2   90.01
  5002.7   90.14  5021.9    98.1    5036      99    5144   98.96    5216    98.6
  5223.8    98.1  5253.8    98.9  5283.8    98.5  5503.8    99.8  5553.8    98.2
  5573.8      99  5731.1    99.5  5923.8   100.1  6073.8    99.2    6237     100
#Mann= 9 , 1 , 0
  3553.4     .12       0  3836.1     .07       0  4536.3      .1       0
  4615.1     .07       0    4966     .05       0  5021.9     .12       0
    5144     .07       0  5731.1      .1       0    6237      .2       0
Bank Sta=4966,5021.9
XS Rating Curve= 0 ,0
Exp/Cntr=0.3,0.1

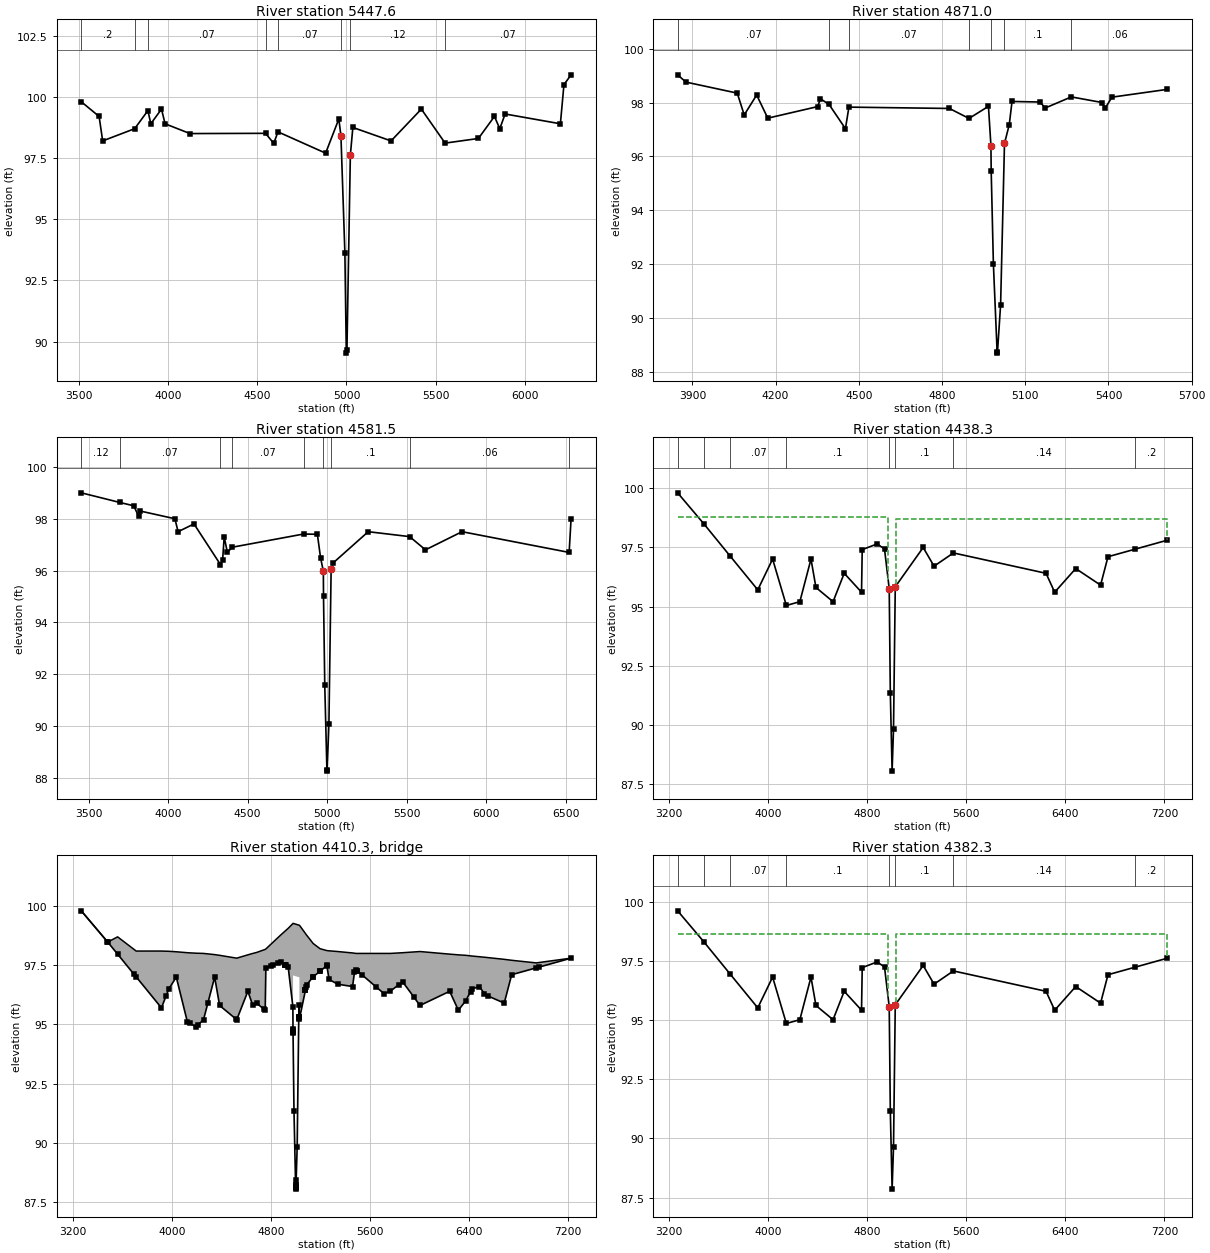
Type RM Length L Ch R = 1 ,5447.6  ,576.3,576.6,577.7
BEGIN DESCRIPTION:
Cross Section  5447.6
END DESCRIPTION:
XS GIS Cut Line= 5
      3096127.65     13914767.54      3095976.37     13913982.32
      3095788.17      13913443.1      3095698.35     13913118.21
      3094938.08     13912408.65
#Sta/Elev= 30
  3512.4    99.8  3612.4    99.2  3632.4    98.2    3812    98.7  3886.3   99.44
  3902.4    98.9  3962.4    99.5  3982.4    98.9  4122.4    98.5    4546   98.51
    4592    98.1  4615.9   98.57  4883.2    97.7  4957.4    99.1  4969.2   98.39
  4991.2   93.63  4999.2   89.53  5002.7   89.66  5021.9   97.62  5035.9   98.75
  5250.2    98.2  5420.2    99.5  5553.5   98.11  5740.2    98.3  5830.2    99.2
  5860.2    98.7  5890.2    99.3  6200.2    98.9  6220.2   100.5  6260.2   100.9
#Mann= 8 , 1 , 0
  3512.4      .2       0    3812     .12       0  3886.3     .07       0
    4546      .1       0  4615.9     .07       0  4969.2     .05       0
  5021.9     .12       0  5553.5     .07       0
Bank Sta=4969.2,5021.9
XS Rating Curve= 0 ,0
Exp/Cntr=0.3,0.1

Type RM Length L Ch R = 1 ,4871.0  ,279.6,289.5,299.4
BEGIN DESCRIPTION:
Cross Section  4871.0-Interpolated
END DESCRIPTION:
XS GIS Cut Line= 4
      3096431.42     13914339.43      3096345.48     13913297.35
      3096277.03     13913046.35      3096124.14     13912612.48
#Sta/Elev= 30
  3846.8   99.03  3876.8   98.76  4061.8   98.35  4086.8   97.54  4131.8   98.28
  4171.8   97.42  4351.8   97.85  4361.8   98.14  4392.7   97.93  4451.8   97.03
  4464.3   97.83  4826.8   97.78  4897.3   97.41  4967.4   97.86  4976.3    96.4
  4977.3   95.44  4985.2      92  4998.6   88.75  4999.7   88.69  5011.2   90.49
  5025.2   96.48  5042.4   97.18  5052.4   98.04  5152.6   98.02  5172.6    97.8
  5266.2   98.21  5377.6      98  5387.6   97.78  5412.6    98.2  5612.6   98.49
#Mann= 7 , 1 , 0
  3846.8     .07       0  4392.7      .1       0  4464.3     .07       0
  4897.3      .1       0  4976.3     .05       0  5025.2      .1       0
  5266.2     .06       0
Bank Sta=4976.3,5025.2
XS Rating Curve= 0 ,0
Exp/Cntr=0.3,0.1

Type RM Length L Ch R = 1 ,4581.5  ,140.4,143.2,144.8
BEGIN DESCRIPTION:
Cross Section 4581.5-Interpolated
END DESCRIPTION:
XS GIS Cut Line= 5
       3096512.6     13914652.98      3096659.09     13914314.53
      3096601.31     13913210.19      3096601.31     13913030.41
      3096623.93     13911605.01
#Sta/Elev= 30
  3454.1      99  3695.2   98.63  3784.1    98.5  3814.1    98.1  3822.8    98.3
  4042.8      98  4062.8    97.5  4162.8    97.8  4329.4   96.23  4342.8    96.4
  4352.8    97.3  4372.8    96.7    4403    96.9  4851.9   97.41  4938.7    97.4
  4958.7    96.5  4976.3   95.97  4977.3   95.01  4985.2   91.57  4998.6   88.32
  4999.7   88.26  5011.2   90.06  5025.2   96.05  5038.7    96.3  5258.5    97.5
  5518.8   97.31  5618.5    96.8  5848.5    97.5  6521.9    96.7  6534.1      98
#Mann= 9 , 1 , 0
  3454.1     .12       0  3695.2     .07       0  4329.4      .1       0
    4403     .07       0  4851.9      .1       0  4976.3     .05       0
  5025.2      .1       0  5518.8     .06       0  6521.9      .2       0
Bank Sta=4976.3,5025.2
XS Rating Curve= 0 ,0
Exp/Cntr=0.5,0.3

Type RM Length L Ch R = 1 ,4438.3  ,56,56,56
BEGIN DESCRIPTION:
Upstream Section of Bridge/Culvert/Weir
END DESCRIPTION:
XS GIS Cut Line= 5
      3096666.28     13914859.81      3096737.09     13913387.32
      3096758.05     13912926.17       3096779.2     13912477.72
      3096852.42     13910907.49
#Sta/Elev= 30
    3267   99.81  3480.5   98.49    3694   97.12  3914.4   95.71  4034.4   97.01
  4145.3   95.05  4254.4   95.21  4344.4   97.01  4384.4   95.81  4522.7   95.21
  4612.7   96.41  4752.7   95.61  4758.2   97.41  4878.5   97.65  4938.2   97.44
  4976.3   95.76  4985.2   91.36  4999.7   88.05  5011.1   89.85  5025.2   95.84
  5250.7    97.5  5338.5   96.71  5494.8   97.27    6243   96.41    6313   95.61
    6483   96.61  6683.7   95.91  6743.7   97.11  6963.3   97.43  7223.7   97.81
#Mann= 8 , 1 , 0
    3267      .2       0  3480.5     .12       0    3694     .07       0
  4145.3      .1       0  4976.3     .05       0  5025.2      .1       0
  5494.8     .14       0  6963.3      .2       0
#XS Ineff= 2 , 0
       0    4968    98.8    5034       0    98.7
Permanent Ineff=
       F       F
Bank Sta=4976.3,5025.2
XS Rating Curve= 0 ,0
Exp/Cntr=0.5,0.3

Type RM Length L Ch R = 3 ,4410.3  ,,,
BEGIN DESCRIPTION:
SPEARS-GEARS ROAD
Structure ID: P46-2
END DESCRIPTION:
Bridge Culvert--1,0,-1,-1, 0
Deck Dist Width WeirC Skew NumUp NumDn MinLoCord MaxHiCord MaxSubmerge Is_Ogee
10,36,2.6,0, 50, 50, , , 0.95, 0, 1,1,,
    3267  3480.5  3560.5  3710.5  3914.4  3974.4  4034.4  4124.4  4194.4  4254.4
  4344.4  4384.4  4522.7  4612.7  4652.7  4682.7  4752.7  4758.2  4878.5  4938.2
  4976.3  4977.3 4977.51  4977.6 5028.99  5029.1  5029.6  5086.4  5140.2  5195.6
  5250.7  5268.5  5338.5  5458.5  5473.8  5483.8    5713    5763    5863    6003
    6243    6313    6373    6423    6483    6523  6683.7  6743.7  6941.8  7223.7
    99.8   98.48    98.7    98.1    98.1   98.09   98.07   98.03   98.01      98
   97.95   97.92    97.8   97.94      98   98.04   98.17   98.19   98.78   99.06
   99.26   99.27   99.27   99.27   99.19   99.19   99.19   98.78   98.42    98.2
   98.12   98.11   98.08   98.02   98.01      98      98      98   98.03   98.08
   97.97   97.94   97.92   97.89   97.86   97.84   97.75   97.71    97.6    97.8
    99.8   98.48   97.97   97.01    95.7    96.5      97    95.1    94.9    95.2
      97    95.8    95.2    96.4    95.8    95.9    95.6    97.4   97.64   97.43
   95.75   94.79    94.7   97.07   96.99   95.31   95.24   96.66   97.02   97.24
   97.49    96.9    96.7    96.6    97.2    97.3    96.3    96.4    96.8    95.8
    96.4    95.6      96    96.5    96.6    96.3    95.9    97.1   97.39    97.8
    3267  3480.5  3560.5  3710.5  3914.4  3974.4  4034.4  4124.4  4194.4  4254.4
  4344.4  4384.4  4522.7  4612.7  4652.7  4682.7  4752.7  4758.2  4878.5  4938.2
  4976.3  4977.3 4977.51  4977.6 5028.99  5029.1  5029.6  5086.4  5140.2  5195.6
  5250.7  5268.5  5338.5  5458.5  5473.8  5483.8    5713    5763    5863    6003
    6243    6313    6373    6423    6483    6523  6683.7  6743.7  6941.8  7223.7
    99.8   98.48    98.7    98.1    98.1   98.09   98.07   98.03   98.01      98
   97.95   97.92    97.8   97.94      98   98.04   98.17   98.19   98.78   99.06
   99.26   99.27   99.27   99.27   99.19   99.19   99.19   98.78   98.42    98.2
   98.12   98.11   98.08   98.02   98.01      98      98      98   98.03   98.08
   97.97   97.94   97.92   97.89   97.86   97.84   97.75   97.71    97.6    97.8
   99.66   98.34   97.83   96.87   95.56   96.36   96.86   94.96   94.76   95.06
   96.86   95.66   95.06   96.26   95.66   95.76   95.46   97.26    97.5   97.29
   95.61   94.65   94.56   96.93   96.85   95.17    95.1   96.52   96.88    97.1
   97.35   96.76   96.56   96.46   97.06   97.16   96.16   96.26   96.66   95.66
   96.26   95.46   95.86   96.36   96.46   96.16   95.76   96.96   97.25   97.66
BR Coef= 1 , 1 , 0 ,1.25, 0 ,,,0.8,0,2,0,
WSPro=,,,, 1 ,,,, 0 ,,,, 0 ,,,,-1 ,-1 ,-1 , 0 , 0 , 0 , 0 , 0
BR U #Sta/Elev= 94
    3267    99.8    3477    98.5  3480.5   98.48  3560.5   97.97    3694   97.11
  3710.5   97.01  3914.4    95.7  3950.5   96.18  3974.4    96.5  4034.4      97
  4124.4    95.1  4145.3   95.04  4194.4    94.9  4210.5   94.98  4254.4    95.2
  4290.5   95.92  4344.4      97  4384.4    95.8  4520.5   95.21  4522.7    95.2
  4612.7    96.4  4652.7    95.8  4682.7    95.9  4743.9   95.64  4752.7    95.6
  4758.2    97.4  4795.7   97.46  4816.2   97.49  4852.5   97.58  4878.5   97.64
  4914.4   97.51 4916.49   97.51  4916.6   97.51 4916.71   97.51  4938.2   97.43
  4976.3   95.75  4977.3   94.79  4977.4   94.75 4977.51    94.7  4977.6   94.66
  4977.7   94.62  4985.2   91.35  4997.5   88.41  4998.4    88.2  4998.6    88.1
  4999.7   88.04  5000.1   88.14  5001.6   88.21  5011.1   89.84  5025.2   95.83
  5028.9   95.33 5028.99   95.32  5029.1   95.31  5029.2   95.29  5029.6   95.24
 5077.59   96.44  5077.7   96.44 5077.81   96.45  5083.3   96.58  5086.4   96.66
  5140.2   97.02  5140.5   97.02  5195.6   97.24  5197.8   97.25  5250.7   97.49
  5251.6   97.46  5268.5    96.9  5338.5    96.7  5458.5    96.6  5473.8    97.2
  5483.8    97.3  5492.9   97.26  5494.8   97.26  5533.8    97.1  5651.8   96.57
    5713    96.3    5763    96.4  5831.8   96.68    5863    96.8  5951.8   96.17
    6003    95.8    6243    96.4    6313    95.6    6373      96  6411.8   96.39
    6423    96.5    6483    96.6    6523    96.3    6553    96.2  6683.7    95.9
  6743.7    97.1  6941.8   97.39  6963.3   97.42  7223.7    97.8
BR U #Mann= 8
    3267      .2  3480.5     .12    3694     .07  4145.3      .1  4976.3     .05
  5025.2      .1  5494.8     .14  6963.3      .2
BR U Banks=4976.3,5025.2
BR D #Sta/Elev= 94
    3267   99.66    3477   98.36  3480.5   98.34  3560.5   97.83    3694   96.97
  3710.5   96.87  3914.4   95.56  3950.5   96.04  3974.4   96.36  4034.4   96.86
  4124.4   94.96  4145.3    94.9  4194.4   94.76  4210.5   94.84  4254.4   95.06
  4290.5   95.78  4344.4   96.86  4384.4   95.66  4520.5   95.07  4522.7   95.06
  4612.7   96.26  4652.7   95.66  4682.7   95.76  4743.9    95.5  4752.7   95.46
  4758.2   97.26  4795.7   97.32  4816.2   97.35  4852.5   97.44  4878.5    97.5
  4914.4   97.37 4916.49   97.37  4916.6   97.37 4916.71   97.37  4938.2   97.29
  4976.3   95.61  4977.3   94.65  4977.4   94.61 4977.51   94.56  4977.6   94.52
  4977.7   94.48  4985.2   91.21  4997.5   88.27  4998.4   88.06  4998.6   87.96
  4999.7    87.9  5000.1      88  5001.6   88.07  5011.1    89.7  5025.2   95.69
  5028.9   95.19 5028.99   95.18  5029.1   95.17  5029.2   95.15  5029.6    95.1
 5077.59    96.3  5077.7    96.3 5077.81   96.31  5083.3   96.44  5086.4   96.52
  5140.2   96.88  5140.5   96.88  5195.6    97.1  5197.8   97.11  5250.7   97.35
  5251.6   97.32  5268.5   96.76  5338.5   96.56  5458.5   96.46  5473.8   97.06
  5483.8   97.16  5492.9   97.12  5494.8   97.12  5533.8   96.96  5651.8   96.43
    5713   96.16    5763   96.26  5831.8   96.54    5863   96.66  5951.8   96.03
    6003   95.66    6243   96.26    6313   95.46    6373   95.86  6411.8   96.25
    6423   96.36    6483   96.46    6523   96.16    6553   96.06  6683.7   95.76
  6743.7   96.96  6941.8   97.25  6963.3   97.28  7223.7   97.66
BR D #Mann= 8
    3267      .2  3480.5     .12    3694     .07  4145.3      .1  4976.3     .05
  5025.2      .1  5494.8     .14  6963.3      .2
BR D Banks=4976.3,5025.2
BC Design=,, 0 ,, 0 ,,,,,,
BC HTab HWMax=99.81
BC Use User HTab Curves=0
BC User HTab FreeFlow(D)= 0

Type RM Length L Ch R = 1 ,4382.3  ,743.7,743.7,743.7
BEGIN DESCRIPTION:
Downstream Section of Bridge/Culvert/Weir
END DESCRIPTION:
XS GIS Cut Line= 5
      3096722.28     13914860.39      3096793.09      13913387.9
      3096814.05     13912926.75       3096835.2      13912478.3
      3096908.42     13910908.07
#Sta/Elev= 30
    3267   99.62  3480.5    98.3    3694   96.93  3914.4   95.52  4034.4   96.82
  4145.3   94.86  4254.4   95.02  4344.4   96.82  4384.4   95.62  4522.7   95.02
  4612.7   96.22  4752.7   95.42  4758.2   97.22  4878.5   97.46  4938.2   97.25
  4976.3   95.57  4985.2   91.17  4999.7   87.86  5011.1   89.66  5025.2   95.65
  5250.7   97.31  5338.5   96.52  5494.8   97.08    6243   96.22    6313   95.42
    6483   96.42  6683.7   95.72  6743.7   96.92  6963.3   97.24  7223.7   97.62
#Mann= 8 , 1 , 0
    3267      .2       0  3480.5     .12       0    3694     .07       0
  4145.3      .1       0  4976.3     .05       0  5025.2      .1       0
  5494.8     .14       0  6963.3      .2       0
#XS Ineff= 2 , 0
       0    4968   98.65    5034       0   98.65
Permanent Ineff=
       F       F
Bank Sta=4976.3,5025.2
XS Rating Curve= 0 ,0
Exp/Cntr=0.5,0.3