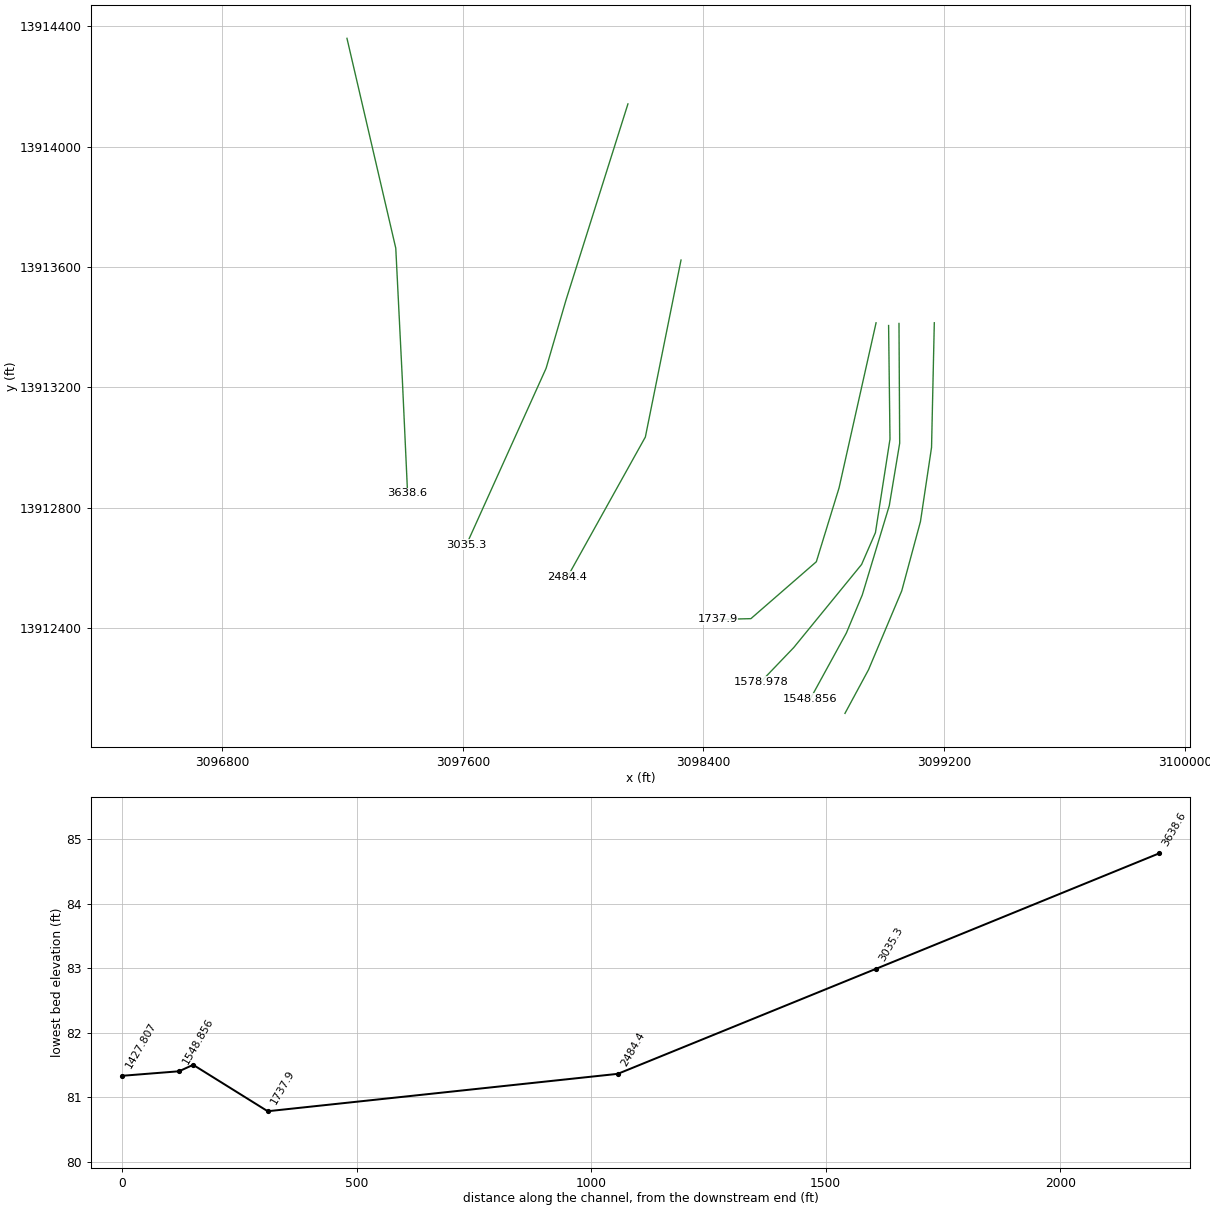
HEC-RAS study P146-00-00.prj: P146-00-00

--- P146-00-00.g01 (geometry) --- (continued)

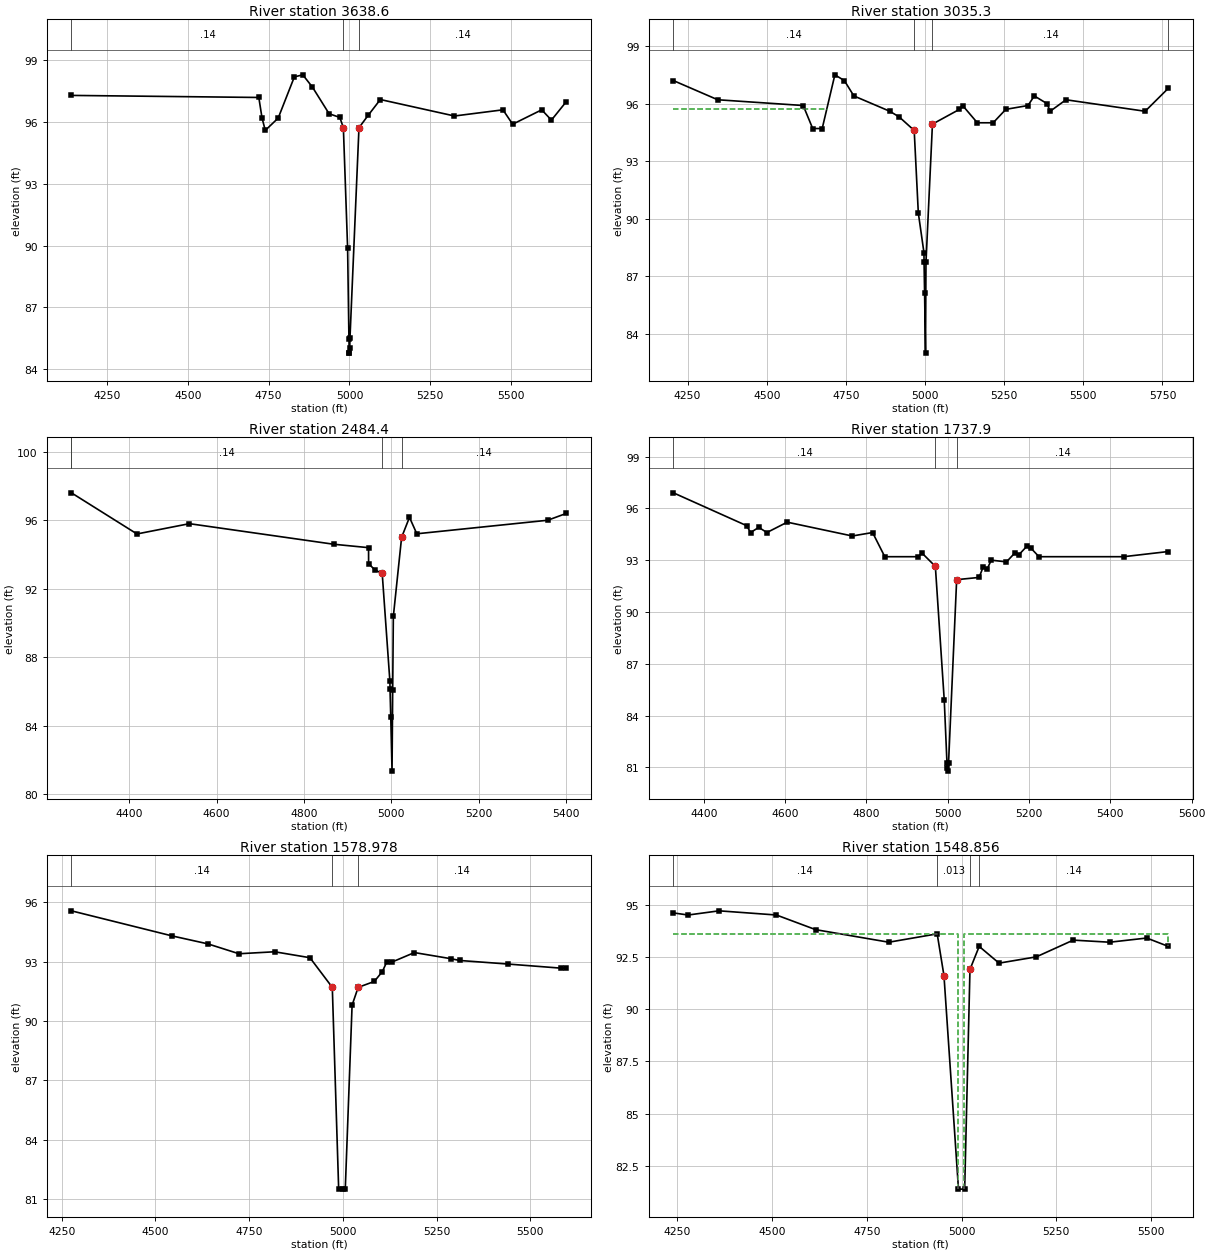
Type RM Length L Ch R = 1 ,3638.6  ,603.2,603.3,589.7
BEGIN DESCRIPTION:
Cross Section  3638.6
END DESCRIPTION:
XS GIS Cut Line= 4
      3097215.07     13914360.55      3097377.31     13913663.06
      3097399.26     13913224.09      3097416.54     13912848.33
#Sta/Elev= 26
  4139.5    97.3  4719.5    97.2  4729.5    96.2  4739.5    95.6  4779.5    96.2
  4829.5    98.2  4855.6    98.3  4885.6    97.7    4937   96.41  4970.3   96.23
  4981.2   95.73  4994.3   89.89  4998.4   85.49  4999.5   84.78  4999.8   84.79
  5000.9   85.03  5001.6    85.5  5029.5   95.73  5057.8   96.33  5095.6    97.1
  5325.1    96.3  5475.1    96.6  5505.1    95.9  5595.1    96.6  5625.1    96.1
  5671.3      97
#Mann= 3 , 1 , 0
  4139.5     .14       0  4981.2     .07       0  5029.5     .14       0
Bank Sta=4981.2,5029.5
XS Rating Curve= 0 ,0
Exp/Cntr=0.3,0.1

Type RM Length L Ch R = 1 ,3035.3  ,554,550.9,535
BEGIN DESCRIPTION:
Cross Section 3035.3-Interpolated
END DESCRIPTION:
XS GIS Cut Line= 4
      3098149.03     13914142.55      3097943.16     13913490.63
      3097876.97     13913263.69      3097612.21     13912677.44
#Sta/Elev= 30
  4205.2    97.2  4345.2    96.2  4615.2    95.9  4645.2    94.7  4675.2    94.7
  4715.2    97.5  4745.2    97.2  4775.2    96.4  4888.8    95.6  4918.8    95.3
  4965.8    94.6  4978.8    90.3  4996.6   88.23  4996.9   87.76  4998.6   86.14
  5001.5   82.99    5003   87.72  5023.4   94.93  5108.8    95.7  5118.8    95.9
  5165.2      95  5215.2      95  5255.2    95.7  5325.2    95.9  5345.2    96.4
  5385.2      96  5395.2    95.6  5445.2    96.2  5695.2    95.6  5768.5    96.8
#Mann= 4 , 1 , 0
  4205.2     .14       0  4965.8     .07       0  5023.4     .14       0
  5768.5      .2       0
#XS Ineff= 2 , 0
       0    4689    95.7  5125.4       0    95.7
Permanent Ineff=
       F       F
Bank Sta=4965.8,5023.4
XS Rating Curve= 0 ,0
Exp/Cntr=0.3,0.1

Type RM Length L Ch R = 1 ,2484.4  ,701.7,746.5,751.3
BEGIN DESCRIPTION:
Cross Section  2484.4
END DESCRIPTION:
XS GIS Cut Line= 3
      3098325.47     13913623.55      3098206.95     13913035.34
      3097947.96     13912570.04
#Sta/Elev= 19
  4267.8    97.6  4417.8    95.2  4537.8    95.8  4867.8    94.6  4947.8    94.4
  4947.9   93.47  4962.3    93.1    4979    92.9  4996.6    86.6  4996.9   86.13
  4998.6   84.51  5001.5   81.36    5003   86.09  5004.5   90.39  5023.4      95
  5041.4   96.17  5058.2   95.21  5357.8      96  5400.4    96.4
#Mann= 4 , 1 , 0
  4267.8      .2       0  4267.8     .14       0    4979     .07       0
  5023.4     .14       0
Bank Sta=4979,5023.4
XS Rating Curve= 0 ,0
Exp/Cntr=0.3,0.1

Type RM Length L Ch R = 1 ,1737.9  ,161.7,158.922,154.9
BEGIN DESCRIPTION:
Cross Section 1737.9-Interpolated
END DESCRIPTION:
XS GIS Cut Line= 5
      3098973.83     13913414.98       3098850.9     13912866.55
      3098775.26      13912620.7      3098557.78     13912431.59
      3098447.74     13912428.77
#Sta/Elev= 30
  4325.1    96.9  4505.1      95  4515.1    94.6  4535.1    94.9  4555.1    94.6
  4605.1    95.2  4765.1    94.4  4815.1    94.6  4845.1    93.2  4927.1    93.2
  4937.1    93.4  4969.5   92.64  4991.4   84.88  4998.1   81.24  4998.3   80.98
  4999.4   80.78  5001.9   81.23  5021.9   91.87  5077.1      92  5087.1    92.6
  5097.1    92.5  5107.1      93  5144.4    92.9  5164.4    93.4  5174.4    93.3
  5194.4    93.8  5204.4    93.7  5224.4    93.2  5432.6    93.2  5542.6    93.5
#Mann= 3 ,-1 , 0
  4325.1     .14       0  4969.5     .07       0  5021.9     .14       0
Bank Sta=4969.5,5021.9
XS Rating Curve= 0 ,0
Exp/Cntr=0.3,0.1

Type RM Length L Ch R = 1 ,1578.978,20.6,30.122,31.9
BEGIN DESCRIPTION:
EHRA Add'l X-Sect (April 2011)
EHRA Survey Data used for Channel and Adjacent Overbank Area
EHRA LiDAR Data used for remaining unsurveyed Overbanks
END DESCRIPTION:
XS GIS Cut Line= 6
  3099015.48950813913405.8954169 3099020.093840913913028.3401179
 3098971.748345413912717.5476462 3098925.705016213912611.6479892
 3098700.092703413912335.3880143 3098591.890879913912222.5818579
#Sta/Elev= 22
  4275.8   95.57  4544.8    94.3  4639.8    93.9  4722.9    93.4    4818    93.5
  4912.2    93.2  4971.9    91.7  4988.9    81.5    5000    81.5  5006.5    81.5
  5024.7    90.8  5040.9    91.7    5084      92  5105.5    92.5 5116.84   92.97
  5129.9   92.97 5191.03   93.46 5288.29   93.15    5312   93.06 5440.07   92.88
 5583.32   92.67 5596.38   92.69
#Mann= 3 ,-1 , 0
  4275.8     .14       0  4971.9    .013       0  5040.9     .14       0
Bank Sta=4971.9,5040.9
XS Rating Curve= 0 ,0
Exp/Cntr=0.3,0.1

Type RM Length L Ch R = 1 ,1548.856,122.7,121.049,124.1
BEGIN DESCRIPTION:
EHRA Add'l X-Sect April 2011)
EHRA Survey Data used for Overbanks
EHRA Survey Data used for Channel
END DESCRIPTION:
XS GIS Cut Line= 6
 3099050.022004913913412.8019163 3099052.324171313913014.5271192
 3099017.791674513912807.3321381 3098928.007182713912510.3526651
 3098875.057354113912383.7335099 3098755.344698413912165.0276965
#Sta/Elev= 18
 4239.65    94.6 4278.55    94.5 4360.15    94.7 4511.55    94.5 4615.05    93.8
 4808.05    93.2 4935.65    93.6 4953.55    91.6 4991.85    81.4 5008.15    81.4
 5022.15    91.9 5046.45      93 5098.85    92.2 5197.15    92.5 5294.65    93.3
 5390.75    93.2 5488.55    93.4 5545.52      93
#Mann= 4 ,-1 , 0
 4239.65     .14       0 4935.65    .013       0 5022.15     .04       0
 5046.45     .14       0
#XS Ineff= 2 , 0
 4239.65 4991.85   93.61 5007.55 4239.65    93.6
Permanent Ineff=
       F       F
Bank Sta=4953.55,5022.15
XS Rating Curve= 0 ,0
Exp/Cntr=0.5,0.3

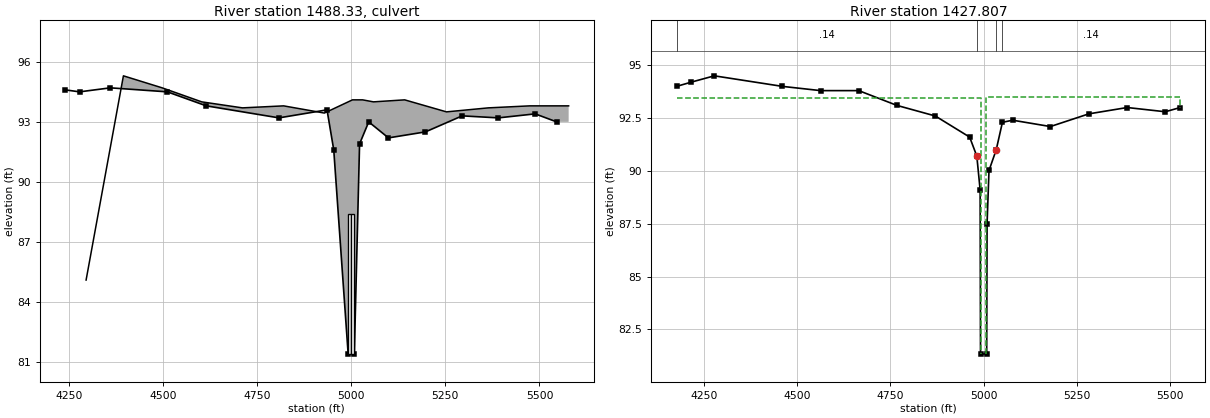
Type RM Length L Ch R = 2 ,1488.33 ,,,
BEGIN DESCRIPTION:
Culvert Crossing at Ella Blvd
END DESCRIPTION:
Bridge Culvert--1,0,-1,-1, 0
Deck Dist Width WeirC Skew NumUp NumDn MinLoCord MaxHiCord MaxSubmerge Is_Ogee
0.025,121,2.6,0, 15, 15, 92, , 0.95, 0, 0,0,,
 4295.75 4394.85 4497.75 4602.85 4711.05 4820.45 4928.55 5003.25 5030.25 5058.95
 5141.95 5252.95 5364.05 5473.95 5577.45
    85.1    95.3    94.7      94    93.7    93.8   93.44    94.1    94.1      94
    94.1    93.5    93.7    93.8    93.8
                                                                                
                                        
  4231.9    4331  4433.9    4539  4647.2  4756.6  4864.7  4939.4  4966.4  4995.1
  5078.1  5189.1  5300.2  5410.1  5527.8
    85.1    95.3    94.7      94    93.7    93.8   93.44    94.1    94.1      94
    94.1    93.5    93.7    93.8    93.8
                                                                                
                                        
Multiple Barrel Culv=2,7,7,121,0.013,0.5,1,10,1,81.4,81.3, 2,Culvert #1  , 2 ,0.025
 4995.35  4995.4 5004.05  5004.1
Culvert Bottom n=0.013
BC Design=,, 0 ,, 0 ,,,,,,
BC HTab HWMax=94.7
BC Use User HTab Curves=0
BC User HTab FreeFlow(D)= 0

Type RM Length L Ch R = 1 ,1427.807,116.1,87.345,43.8
BEGIN DESCRIPTION:
EHRA Add'l X-Sect (April 2011)
EHRA Survey Data used for Overbanks
EHRA Survey Data used for Channel
END DESCRIPTION:
XS GIS Cut Line= 6
 3099167.432494213913415.1040828 3099158.223828413913000.7141205
  3099121.38916513912754.3823095 3099059.230670713912524.1656638
 3098948.726680813912261.7186877 3098870.453021213912116.6822009
#Sta/Elev= 23
  4175.8      94  4214.9    94.2  4277.2    94.5  4460.1      94  4562.6    93.8
  4664.9    93.8  4767.4    93.1  4870.3    92.6  4962.6    91.6  4981.8    90.7
  4990.7    89.1  4991.7   81.33  5008.3   81.34  5009.3    87.5  5014.5   90.02
  5033.9      91  5050.5    92.3    5078    92.4  5179.3    92.1  5282.4    92.7
  5385.5      93  5487.7    92.8 5527.84      93
#Mann= 4 ,-1 , 0
  4175.8     .14       0  4981.8    .013       0  5033.9     .04       0
  5050.5     .14       0
#XS Ineff= 2 , 0
  4175.8  4991.9   93.44  5007.6  4175.8    93.5
Permanent Ineff=
       F       F
Bank Sta=4981.8,5033.9
XS Rating Curve= 0 ,0
Exp/Cntr=0.5,0.3