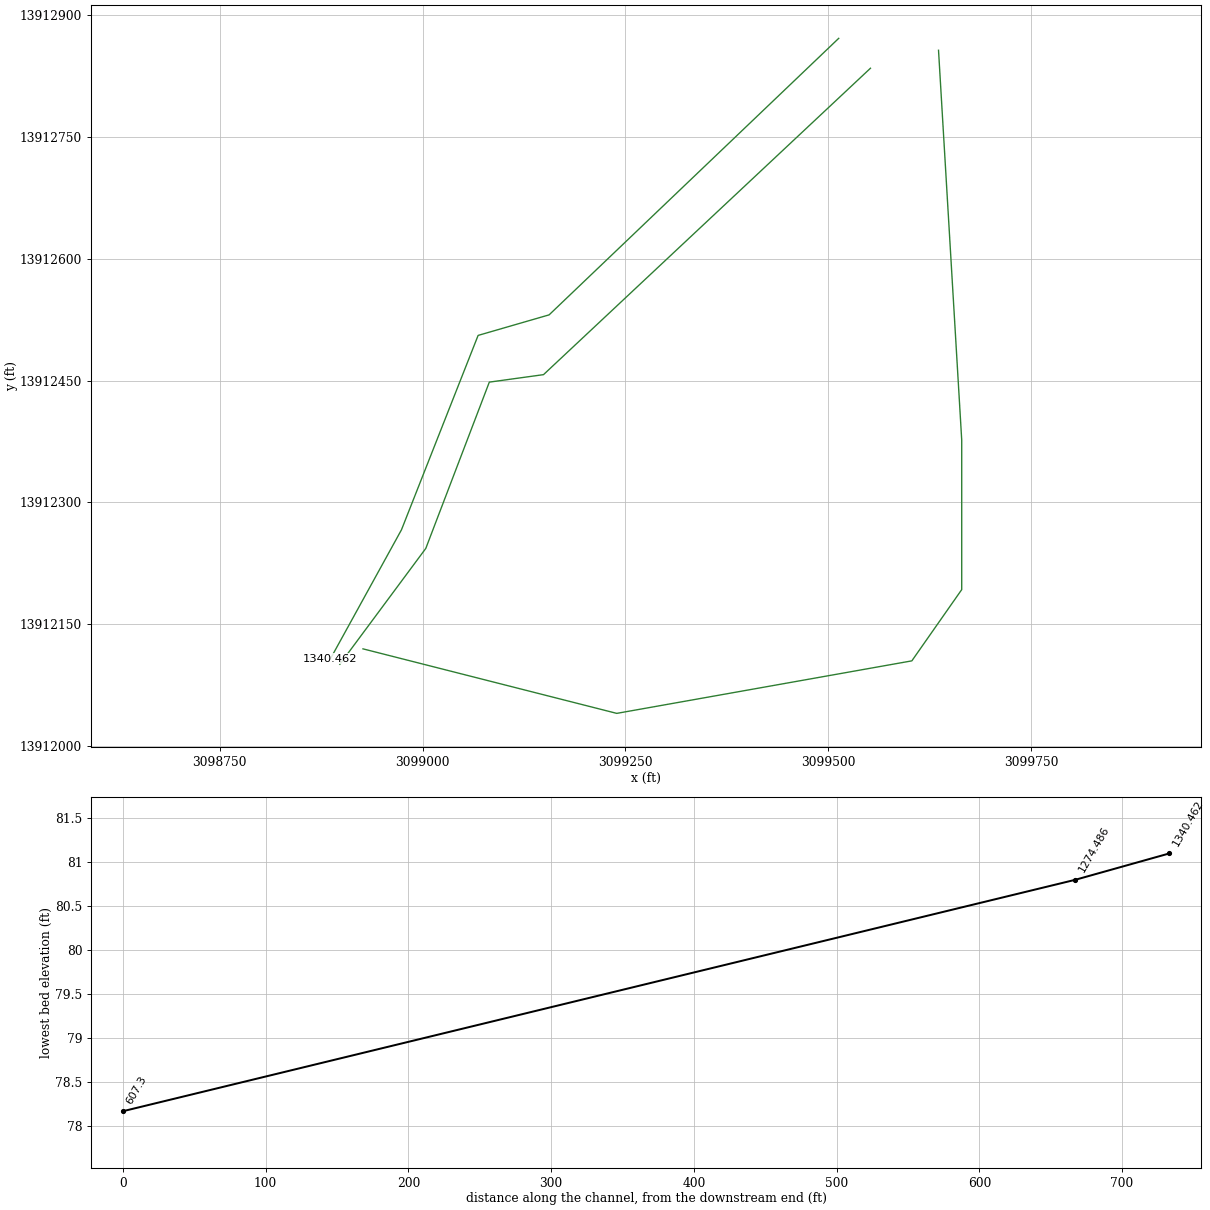
HEC-RAS study P146-00-00.prj: P146-00-00

--- P146-00-00.g01 (geometry) --- (continued)

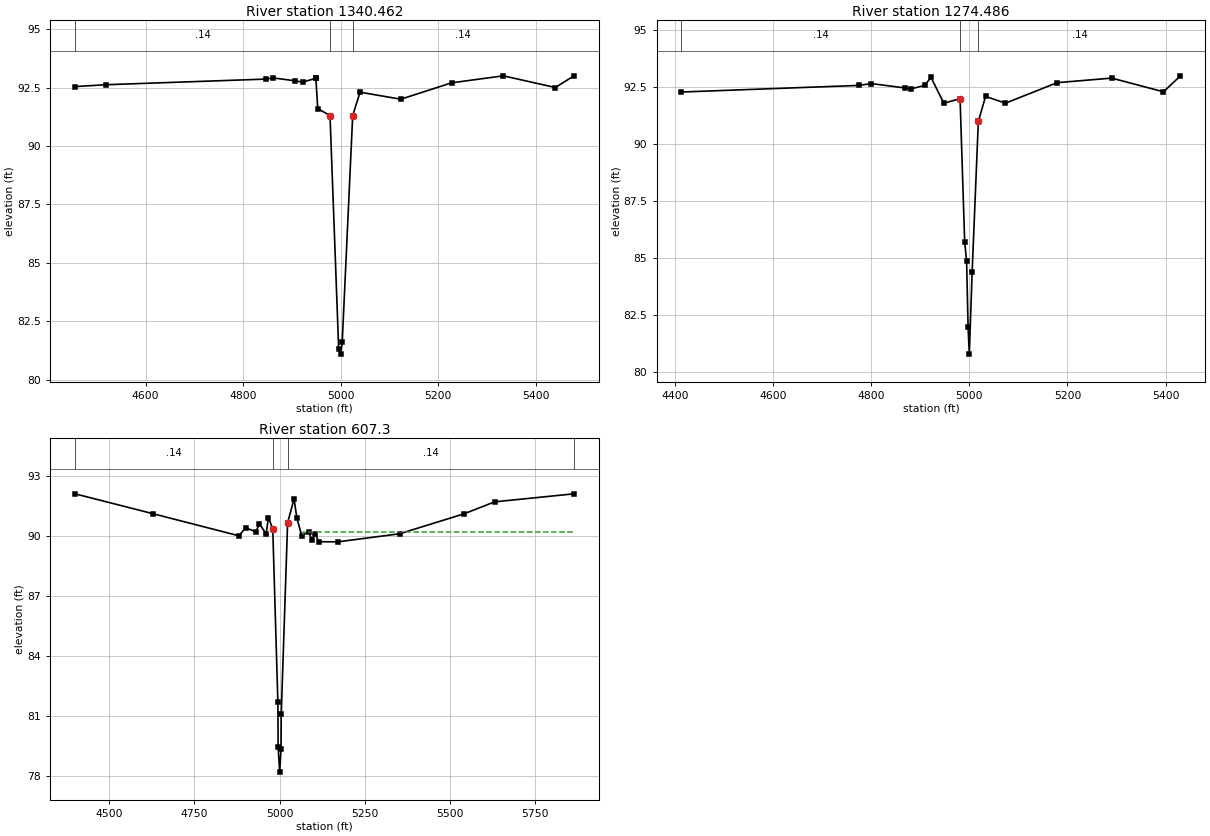
Type RM Length L Ch R = 1 ,1340.462,60.4,65.976,61.3
BEGIN DESCRIPTION:
EHRA Add'l X-Sect (April 2011)
EHRA Survey Data used for Right Overbank
EHRA LiDAR Data used for Left Overbank
EHRA Survey Data used for Channel
END DESCRIPTION:
XS GIS Cut Line= 5
 3099512.757462713912871.7927989 3099155.921661913912531.0721632
 3099068.439336513912505.7483322 3098974.050511813912266.3230206
 3098886.568186413912107.4735351
#Sta/Elev= 20
  4455.1   92.54 4519.28   92.62 4845.97   92.86 4861.67   92.91 4905.34   92.79
  4921.6   92.73 4948.48   92.89 4949.03   92.89  4952.8    91.6    4978    91.3
  4995.8    81.3    5000    81.1    5003    81.6  5024.5    91.3  5039.6    92.3
  5123.2      92  5227.1    92.7  5333.3      93    5440    92.5 5478.26      93
#Mann= 3 , 0 , 0
  4455.1     .14       0    4978     .04       0  5024.5     .14       0
Bank Sta=4978,5024.5
XS Rating Curve= 0 ,0
Exp/Cntr=0.3,0.1

Type RM Length L Ch R = 1 ,1274.486,581.9,667.186,697.1
BEGIN DESCRIPTION:
EHRA Add'l X-Sect (April 2011)
EHRA Survey Data used for Right Overbank
EHRA LiDAR Data used for Left Overbank
EHRA Survey Data used for Channel
Cross-Section Replaced River Station 1284.9
END DESCRIPTION:
XS GIS Cut Line= 5
 3099551.894292613912834.9581355 3099149.015162513912457.4028366
 3099082.252335313912448.1941707 3099003.9786757 13912243.301356
 3098898.079018713912100.5670357
#Sta/Elev= 21
  4413.6   92.29 4775.58   92.58 4800.22   92.66 4868.33   92.47 4881.85   92.43
 4909.03   92.58 4921.98   92.93  4948.1    91.8  4981.2      92  4990.6    85.7
  4994.5    84.9  4997.5      82    5000    80.8  5005.8    84.4  5018.4      91
  5033.2    92.1  5073.6    91.8  5178.9    92.7  5290.1    92.9  5395.6    92.3
  5430.2      93
#Mann= 3 , 0 , 0
  4413.6     .14       0  4981.2     .07       0  5018.4     .14       0
Bank Sta=4981.2,5018.4
XS Rating Curve= 0 ,0
Exp/Cntr=0.3,0.1

Type RM Length L Ch R = 1 ,607.3   ,0,0,0
BEGIN DESCRIPTION:
Cross Section 607.3
END DESCRIPTION:
XS GIS Cut Line= 6
      3099635.73     13912857.09      3099664.31      13912376.9
      3099664.31     13912192.53      3099602.85     13912104.74
      3099239.28     13912040.04      3098926.55     13912119.55
#Sta/Elev= 27
  4399.6    92.1  4629.6    91.1  4880.6      90  4900.6    90.4  4930.6    90.2
  4940.6    90.6  4960.6    90.1  4967.4   90.91    4980   90.35    4995   81.68
  4995.8   79.42  5000.4   78.17  5004.3   79.33  5004.9   81.06  5023.6   90.65
  5042.5   91.85  5050.6    90.9    5065      90    5085    90.2    5095    89.8
    5105    90.1    5115    89.7  5172.2    89.7  5352.2    90.1  5541.5    91.1
  5631.5    91.7  5864.1    92.1
#Mann= 4 ,-1 , 0
  4399.6     .14       0    4980     .07       0  5023.6     .14       0
  5864.1      .2       0
#XS Ineff= 2 , 0
       0                  5067.6       0    90.2
Permanent Ineff=
       F       F
Bank Sta=4980,5023.6
XS Rating Curve= 0 ,0
Exp/Cntr=0.3,0.1

Chan Stop Cuts=-1
Use User Specified Reach Order=0
Composite Channel Slope=5